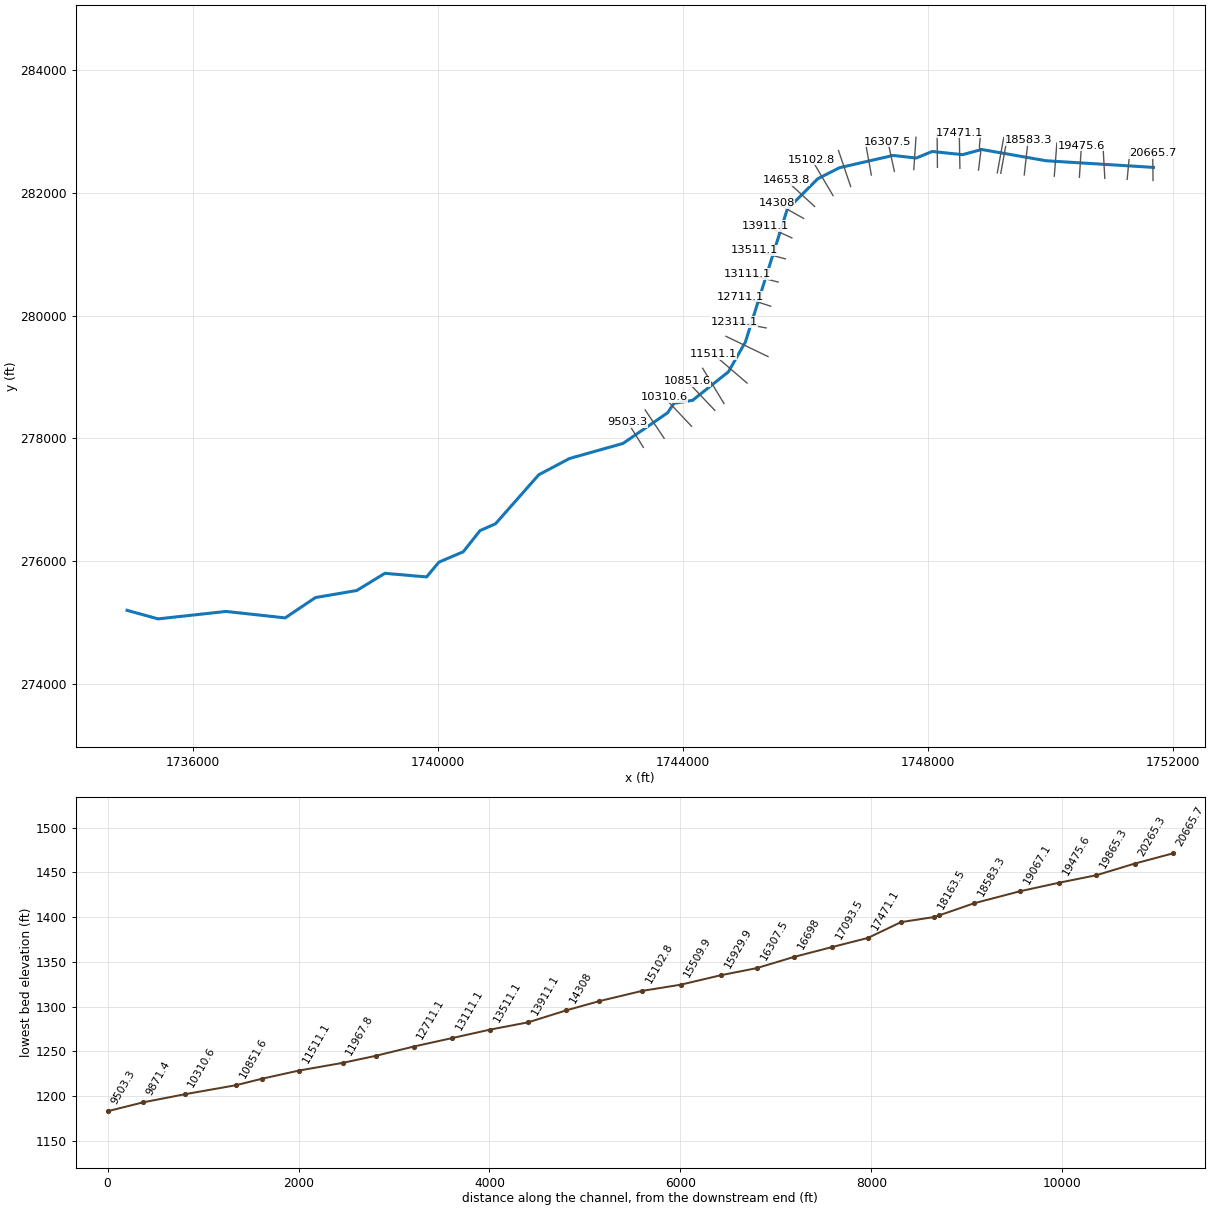
--- RIGHTBFLCK.prj (project) ---

Proj Title=RIGHTBFLCK
Current Plan=p01
Default Exp/Contr=0,0
English Units
Geom File=g01
Flow File=f01
Plan File=p01
BEGIN DESCRIPTION:
END DESCRIPTION:
DSS Export Rating Curves= 0
DSS Export Rating Curve Sorted= 0
DSS Export Volume Flow Curves= 0
DXF OffsetX= 0
DXF OffsetY= 0
DXF ScaleX= 0
DXF ScaleY= 0

--- RIGHTBFLCK.p01 (plan) ---

Plan Title=Floodplain
Program Version=4.00
Geom File=g01
Flow File=f01
K Sum by GR=0
Std Step Tol=0.01
Critical Tol=0.01
Num of Std Step Trials=20
Max Error Tol=0.3
Flow Tol Ratio=0.001
Split Flow NTrial=30
Split Flow Tol=0.02
Split Flow Ratio=0.02
Log Output Level=0
Friction Slope Method=1
Unsteady Friction Slope Method=2
Unsteady Bridges Friction Slope Method=1
Global Log Level=0
CheckData=False
Run HTab=0
Run UNet=0
Run PostProcess=0
UNET Theta=0
UNET Theta Warmup=0
UNET ZTol=0
UNET ZSATol=0
UNET MxIter=0
UNET MaxInSteps=0
UNET DtIC=0
UNET DtMin=0
UNET MaxCRTS=0
UNET WFStab=0
UNET SFStab=0
UNET WFX=0
UNET SFX=0
UNET DSS MLevel=0
UNET DZMax Abort=0
UNET Convert EG Bridges=0
UNET Use Existing IB Tables=0
UNET Froude Limit=0
UNET Froude Power=0
Write IC File=0
Echo Input=False
Echo Output=False
Write Detailed=0

--- RIGHTBFLCK.f01 (steady flow) ---

Flow Title=NFF Regression Equation
Program Version=4.10
Number of Profiles= 1
Profile Names=P100yr
River Rch & RM=RIGHTBFLCK,Main            ,20665.7
944.7448
River Rch & RM=RIGHTBFLCK,Main            ,20265.3
967.8691
River Rch & RM=RIGHTBFLCK,Main            ,17093.5
1063.337
River Rch & RM=RIGHTBFLCK,Main            ,14653.8
1173.221
River Rch & RM=RIGHTBFLCK,Main            ,11967.8
1255.626
River Rch & RM=RIGHTBFLCK,Main            ,11511.1
1479.372
River Rch & RM=RIGHTBFLCK,Main            ,9118.2
1546.518
River Rch & RM=RIGHTBFLCK,Main            ,6309.8
1716.204
River Rch & RM=RIGHTBFLCK,Main            ,5504.9
1873.951
River Rch & RM=RIGHTBFLCK,Main            ,4784.1
1931.974
Boundary for River Rch & Prof#=RIGHTBFLCK,Main            , 1
Up Type= 0
Dn Type= 1
Dn Known WS=1013.31
DSS Import GetInterval= 0
DSS Import GetPeak= 0
DSS Import FillOption= 0

--- RIGHTBFLCK.g01 (geometry) ---

Geom Title=USGS 10m DEM
Program Version=4.10

River Reach=RIGHTBFLCK      ,Main
Reach XY= 30
      1751676.81      282419.495      1749924.17      282527.822
     1748871.643      282711.362     1748562.221      282627.125
     1748064.216      282679.097     1747803.632      282572.161
     1747426.746      282614.284     1746553.354      282414.987
     1746197.433      282235.181     1745698.613      281736.361
     1745014.826      279570.315     1744736.858       279083.87
     1744153.123       278619.43     1743848.516      278570.786
     1743744.277      278415.587     1743016.926      277916.401
     1742143.641      277670.862     1741642.139      277405.633
     1740935.635      276605.315     1740683.047      276494.844
     1740409.943      276149.809     1740011.106      275979.631
      1739811.02      275738.979     1739129.996      275798.047
     1738671.348      275517.762     1737994.957      275401.942
     1737502.721      275070.696     1736536.779      275176.092
     1735427.221      275054.481     1734919.928      275194.624

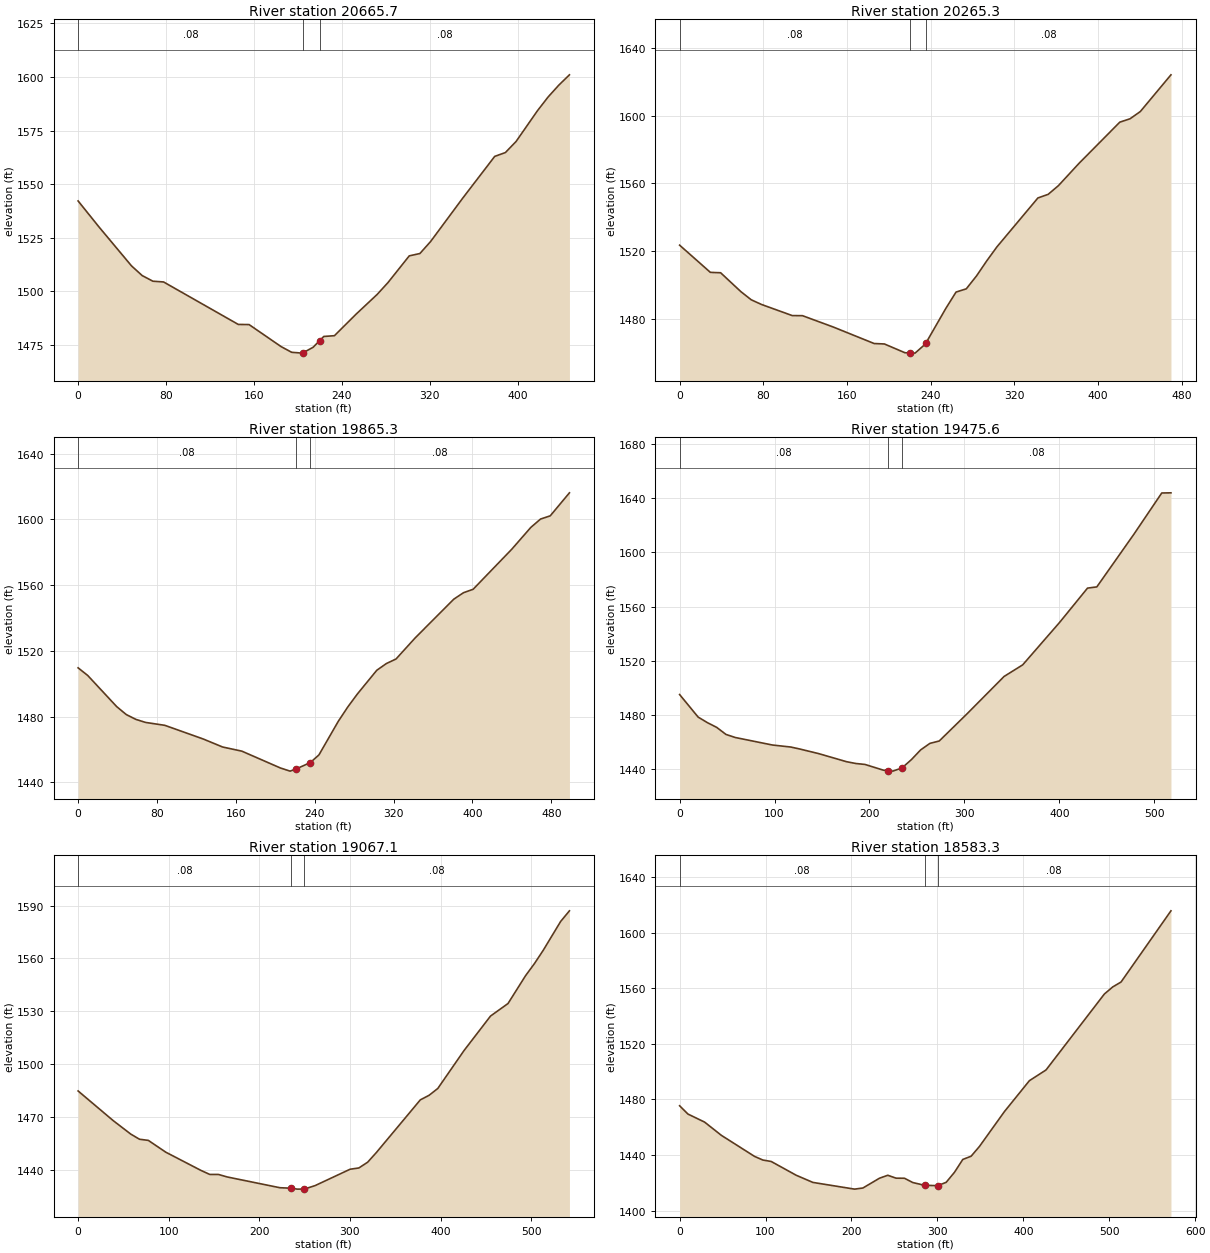
Type RM Length L Ch R = 1 ,20665.7 ,402.8,400.4,397.9
XS GIS Cut Line= 2
     1751670.077       282206.01     1751664.189      282653.197
#Sta/Elev= 30
       0 1542.14    19.4 1529.77    48.6 1511.86    58.3 1507.34    68.1  1504.7
    77.8 1504.36   145.8 1484.54   155.6 1484.48   184.7 1474.22   194.4 1471.54
   204.2 1471.16   204.8 1471.33   213.9 1473.89   219.8 1476.96   223.6 1478.93
   233.3 1479.29   252.8 1489.23   272.2 1498.54     282 1504.04   301.4 1516.52
   311.1 1517.62   320.8 1523.19     350  1543.4   379.2 1562.93   388.9 1564.71
   398.6 1569.86   418.1 1584.23   427.8 1590.64   437.5 1596.14   447.2 1600.97
#Mann= 3 , 0 , 0
       0     .08       0   204.8    .045       0   219.8     .08       0
Bank Sta=204.8,219.8
XS Rating Curve= 0 ,0
Exp/Cntr=0.3,0.1

Type RM Length L Ch R = 1 ,20265.3 ,396.6,400,403.4
XS GIS Cut Line= 2
     1751247.462      282224.384      1751292.15      282692.103
#Sta/Elev= 30
       0  1523.5    29.4 1507.44    39.2 1507.21    58.7 1495.99    68.5 1491.24
    78.3 1488.48   107.7 1481.92   117.5 1481.86   146.8 1475.19     186 1465.42
   195.8 1465.16   215.4 1459.99   220.5 1459.86   225.1 1459.75   234.9 1465.06
   235.5 1465.71   254.5 1486.12   264.3 1495.81   274.1 1497.72   283.9 1505.36
   293.7 1514.26   303.4  1522.5   342.6 1551.39   352.4 1553.52   362.2 1558.65
   381.8 1571.76   420.9 1596.15   430.7 1598.14   440.5 1602.41   469.8 1624.09
#Mann= 3 , 0 , 0
       0     .08       0   220.5    .045       0   235.5     .08       0
Bank Sta=220.5,235.5
XS Rating Curve= 0 ,0
Exp/Cntr=0.3,0.1

Type RM Length L Ch R = 1 ,19865.3 ,392.4,389.7,387
XS GIS Cut Line= 2
     1750882.809      282240.239     1750854.641      282737.855
#Sta/Elev= 30
       0 1509.67     9.8    1505    39.1 1486.09    48.9 1481.21    58.6  1478.3
    68.4 1476.45      88 1474.67     127 1466.34   146.6 1461.48   166.1 1458.96
   205.2 1448.72     215  1446.8   220.6 1447.95   235.6 1452.03   244.3 1456.68
   263.9 1477.09   273.6 1485.89   283.4 1493.84     303  1508.2   312.7 1512.28
   322.5 1515.06     342 1527.94   381.1 1551.47   390.9 1555.39   400.7 1557.49
   439.8  1581.8   459.3 1595.19   469.1 1600.24   478.9 1602.19   498.4  1616.2
#Mann= 3 , 0 , 0
       0     .08       0   220.6    .045       0   235.6     .08       0
Bank Sta=220.6,235.6
XS Rating Curve= 0 ,0
Exp/Cntr=0.3,0.1

Type RM Length L Ch R = 1 ,19475.6 ,408.8,408.5,408.1
XS GIS Cut Line= 2
     1750467.703      282258.287     1750500.752      282774.864
#Sta/Elev= 30
       0 1495.01    19.5 1478.38    29.3 1474.25    39.1 1470.76    48.8 1465.57
    58.6  1463.3    97.7 1457.75   117.2 1456.25     127 1454.72   146.5 1451.39
   175.8 1445.43   185.6  1444.1   195.3 1443.39   214.9 1439.12   219.3 1438.82
   224.6 1438.46   234.3 1440.84   244.2 1446.98   253.9 1454.14   263.7 1458.96
   273.5 1460.72   302.8  1480.8   341.8 1508.38   361.4 1516.94   400.4 1548.39
   429.7 1573.63   439.5 1574.53   478.6 1613.47   507.9 1643.89   517.6 1644.01
#Mann= 3 , 0 , 0
       0     .08       0   219.3    .045       0   234.3     .08       0
Bank Sta=219.3,234.3
XS Rating Curve= 0 ,0
Exp/Cntr=0.3,0.1

Type RM Length L Ch R = 1 ,19067.1 ,484.4,483.7,483.1
XS GIS Cut Line= 2
     1750057.825      282276.108     1750099.955      282816.777
#Sta/Elev= 30
       0 1484.71    38.7 1467.88    58.1 1460.22    67.8 1457.28    77.5 1456.64
    96.8 1449.93   135.6 1439.58   145.3  1437.3     155 1437.27   164.6 1435.86
   222.7 1429.75   234.7 1429.48   242.1 1428.95   249.7    1429   261.5 1430.93
   300.2 1440.25   309.9 1440.98   319.6 1444.25   329.3 1449.79   377.7 1479.65
   387.4 1482.25     397 1486.13   426.1 1507.77   455.2 1527.26   474.5 1534.38
   493.9 1550.22   503.6 1557.01   513.3 1564.56   532.6    1581   542.3 1587.04
#Mann= 3 , 0 , 0
       0     .08       0   234.7    .045       0   249.7     .08       0
Bank Sta=234.7,249.7
XS Rating Curve= 0 ,0
Exp/Cntr=0.3,0.1

Type RM Length L Ch R = 1 ,18583.3 ,364.2,362.6,360.9
XS GIS Cut Line= 2
      1749567.55      282297.424     1749630.709      282865.848
#Sta/Elev= 30
       0 1475.42     9.7 1469.46    29.1 1463.67    48.5 1454.19    87.2    1439
    96.9 1436.39   106.6 1435.35   135.7 1425.44   155.1 1420.29   203.6 1415.46
   213.3 1416.26   232.6  1423.3   242.3 1425.43     252 1423.34   261.7 1423.29
   271.4  1420.2   285.2 1418.19   300.2 1417.98   310.2 1420.32   319.9 1427.55
   329.6 1436.82   339.3 1439.14     349 1446.17     378 1471.19   407.1 1493.45
   426.5  1501.2   494.4 1555.82   504.1  1560.9   513.8 1564.45   571.9 1615.66
#Mann= 3 , 0 , 0
       0     .08       0   285.2    .045       0   300.2     .08       0
#XS Ineff= 2 , 0
          242.61 1424.31
Permanent Ineff=
       F       F
Bank Sta=285.2,300.2
XS Rating Curve= 0 ,0
Exp/Cntr=0.3,0.1

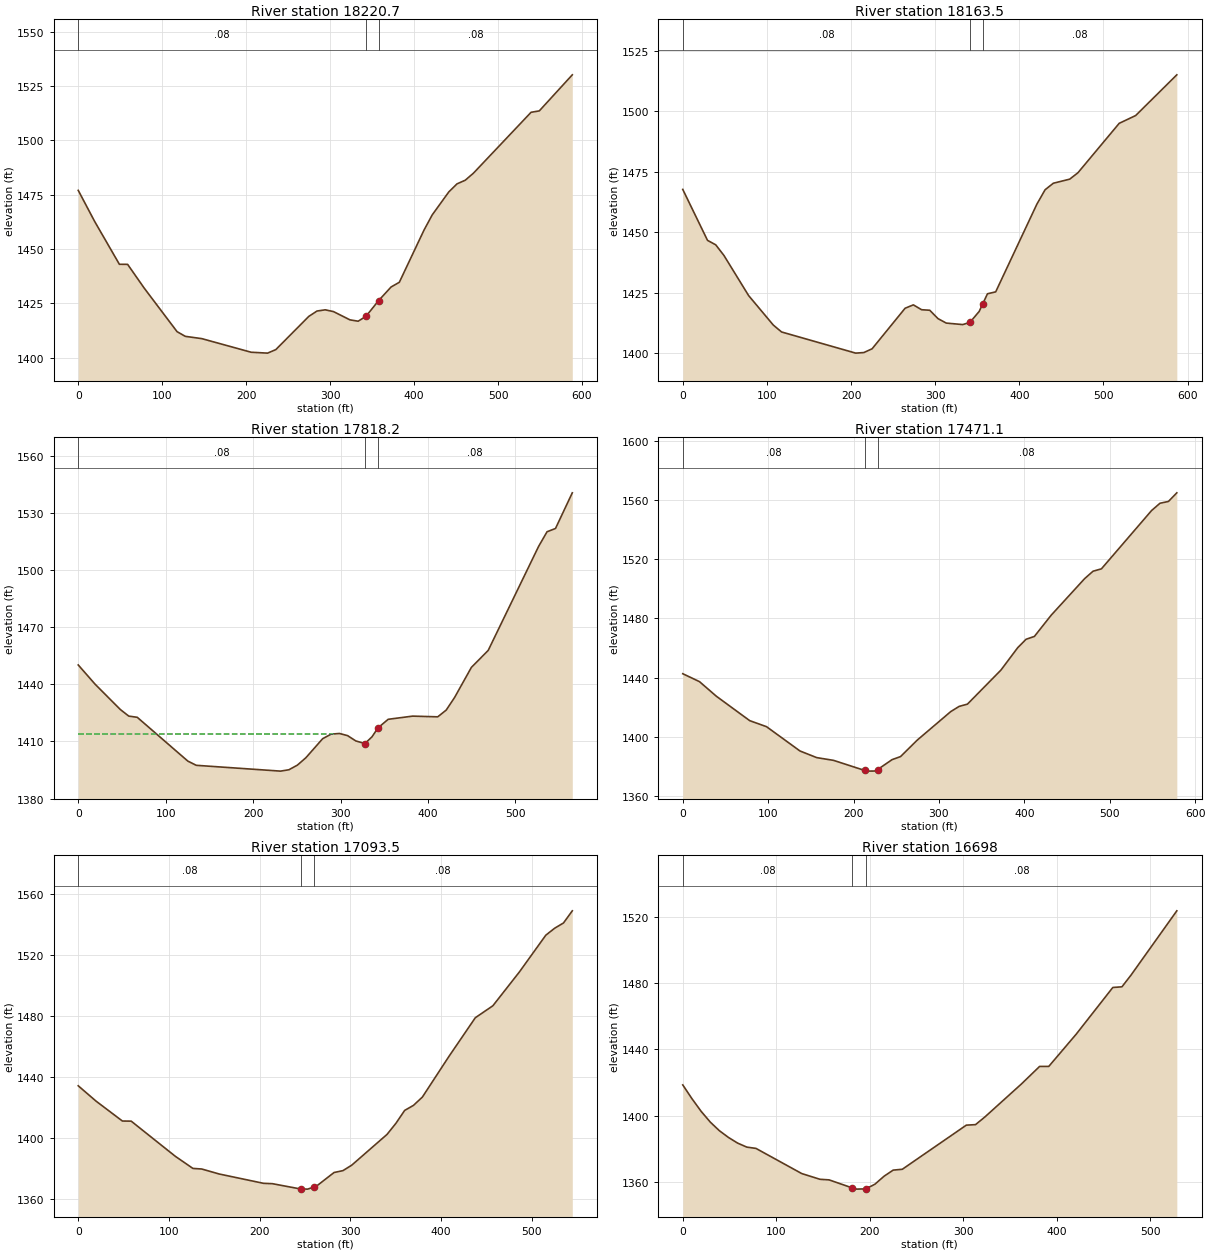
Type RM Length L Ch R = 1 ,18220.7 ,57.1,57.1,57.1
XS GIS Cut Line= 2
     1749183.919      282322.763     1749289.848      282901.494
#Sta/Elev= 30
       0 1477.01    19.6 1462.66      49 1442.97    58.8 1442.94    78.4 1432.08
   117.7 1411.94   127.5 1409.79   147.1 1408.74   205.9 1402.47   225.5 1402.06
   235.3 1403.68   274.6 1418.98   284.4 1421.45   294.2    1422     304 1421.18
   323.6 1417.38   333.4 1416.76   342.7 1419.01   357.7 1426.24   372.6 1432.52
   382.4 1434.68   411.8 1458.71   421.6 1465.73   441.3 1476.28   451.1    1480
   460.9 1481.68   470.7 1484.94   539.3 1512.96   549.1  1513.6   588.4 1530.21
#Mann= 3 , 0 , 0
       0     .08       0   342.7    .045       0   357.7     .08       0
#XS Ineff= 2 , 0
          294.85 1421.39
Permanent Ineff=
       F       F
Bank Sta=342.7,357.7
XS Rating Curve= 0 ,0
Exp/Cntr=0.3,0.1

Type RM Length L Ch R = 1 ,18163.5 ,335,345.4,355.8
XS GIS Cut Line= 2
     1749127.277      282329.746     1749233.016      282907.437
#Sta/Elev= 30
       0 1467.75    29.4  1446.7    39.2 1444.84    48.9 1440.48    78.3 1423.86
   107.7 1411.65   117.5 1408.82   205.6 1400.08   215.3 1400.32   225.1 1401.88
   264.3 1418.63   274.1 1420.03   283.9 1418.02   293.6  1417.8   303.4 1414.34
   313.2  1412.5   332.8 1411.88   341.4  1412.8   352.4 1417.33   356.4  1420.3
   362.2 1424.61     372 1425.41   420.9 1461.62   430.7  1467.6   440.5  1470.3
     460 1471.99   469.8 1474.65   518.8 1495.06   538.4 1498.29   587.3 1515.11
#Mann= 3 , 0 , 0
       0     .08       0   341.4    .045       0   356.4     .08       0
#XS Ineff= 2 , 0
          274.23 1419.76
Permanent Ineff=
       F       F
Bank Sta=341.4,356.4
XS Rating Curve= 0 ,0
Exp/Cntr=0.3,0.1

Type RM Length L Ch R = 1 ,17818.2 ,352.9,347,341.1
XS GIS Cut Line= 4
     1748820.478      282374.645     1748857.619      282671.172
     1748834.667      282751.504     1748851.061      282933.481
#Sta/Elev= 30
       0  1450.1    19.3    1440    48.2  1426.7    57.8 1423.27    67.5 1422.64
   125.3 1399.68     135 1397.45   231.4  1394.4     241 1395.13   250.6 1397.53
   260.3 1401.39   279.6 1411.43   289.2  1413.8   298.8 1414.16   308.1 1413.02
   317.4 1410.26   327.9 1408.86     336  1412.4   342.9 1417.13   354.5 1421.59
   382.4 1423.26   411.2 1422.89   420.9 1426.44   430.5 1433.07   449.7 1448.84
   468.9 1457.73   526.6 1512.34   536.2 1519.98   545.9 1521.72   565.1 1540.42
#Mann= 3 , 0 , 0
       0     .08       0   327.9    .045       0   342.9     .08       0
#XS Ineff= 2 , 0
          292.02 1413.93
Permanent Ineff=
       F       F
Bank Sta=327.9,342.9
XS Rating Curve= 0 ,0
Exp/Cntr=0.3,0.1

Type RM Length L Ch R = 1 ,17471.1 ,377.5,377.6,377.6
XS GIS Cut Line= 2
     1748517.182      282404.963     1748506.443      282983.419
#Sta/Elev= 30
       0 1442.57    19.6 1437.22    39.2 1427.42    78.4 1410.86    98.1 1406.78
   137.3 1390.36   156.9 1385.87   176.5 1384.04   213.2 1377.18   215.7 1376.75
   225.5 1376.83   228.2 1377.83   245.2 1384.54     255 1386.55   274.6 1397.71
   313.8 1416.96   323.6 1420.47   333.4 1422.03   372.6 1445.02   392.2 1460.12
     402 1465.83   411.8 1467.78   431.5 1482.14   470.7 1506.86   480.5 1511.84
   490.3 1513.44   549.1 1552.88   558.9 1557.77   568.8 1558.98   578.6 1564.81
#Mann= 3 , 0 , 0
       0     .08       0   213.2    .045       0   228.2     .08       0
Bank Sta=213.2,228.2
XS Rating Curve= 0 ,0
Exp/Cntr=0.3,0.1

Type RM Length L Ch R = 1 ,17093.5 ,397.7,395.4,393.2
XS GIS Cut Line= 2
     1748150.162       282420.88      1748145.04      282965.863
#Sta/Elev= 30
       0 1434.31    19.5 1424.31    48.7 1411.18    58.4 1411.11   107.1 1388.02
   126.5 1380.07   136.2 1379.69   155.7 1376.38   204.4 1370.29   214.1 1370.06
   245.2 1366.58     253 1366.48   260.2 1367.92   262.8 1368.44   282.2 1377.39
     292 1378.62   301.7 1382.21   340.6 1402.38   350.4 1409.65   360.1 1418.16
   369.8 1421.46   379.6 1426.89   408.8 1453.48     438 1478.98   457.4 1486.85
   486.6    1509   515.8 1533.18   525.5 1537.72   535.3  1541.2     545 1549.16
#Mann= 3 , 0 , 0
       0     .08       0   245.2    .045       0   260.2     .08       0
Bank Sta=245.2,260.2
XS Rating Curve= 0 ,0
Exp/Cntr=0.3,0.1

Type RM Length L Ch R = 1 ,16698   ,384.1,390.5,396.9
XS GIS Cut Line= 2
     1747764.106      282384.112     1747800.477      282911.459
#Sta/Elev= 30
       0 1418.59     9.8 1410.28    19.6 1402.65    29.4 1396.12    39.2 1390.88
    48.9 1386.82    58.7  1383.4    68.5 1380.97    78.3  1380.2   127.3 1364.98
   146.8 1361.52   156.6 1361.16     181 1356.37     186 1355.57     196 1355.76
   205.6 1358.55   215.4 1363.38   225.1 1367.06   234.9 1367.58   303.4 1394.26
   313.2 1394.56     323 1399.08   362.2 1419.08   381.8 1429.76   391.6 1429.76
   420.9 1449.23   460.1 1477.48   469.9  1477.9   479.6 1484.98   528.6 1523.84
#Mann= 3 , 0 , 0
       0     .08       0     181    .045       0     196     .08       0
Bank Sta=181,196
XS Rating Curve= 0 ,0
Exp/Cntr=0.3,0.1

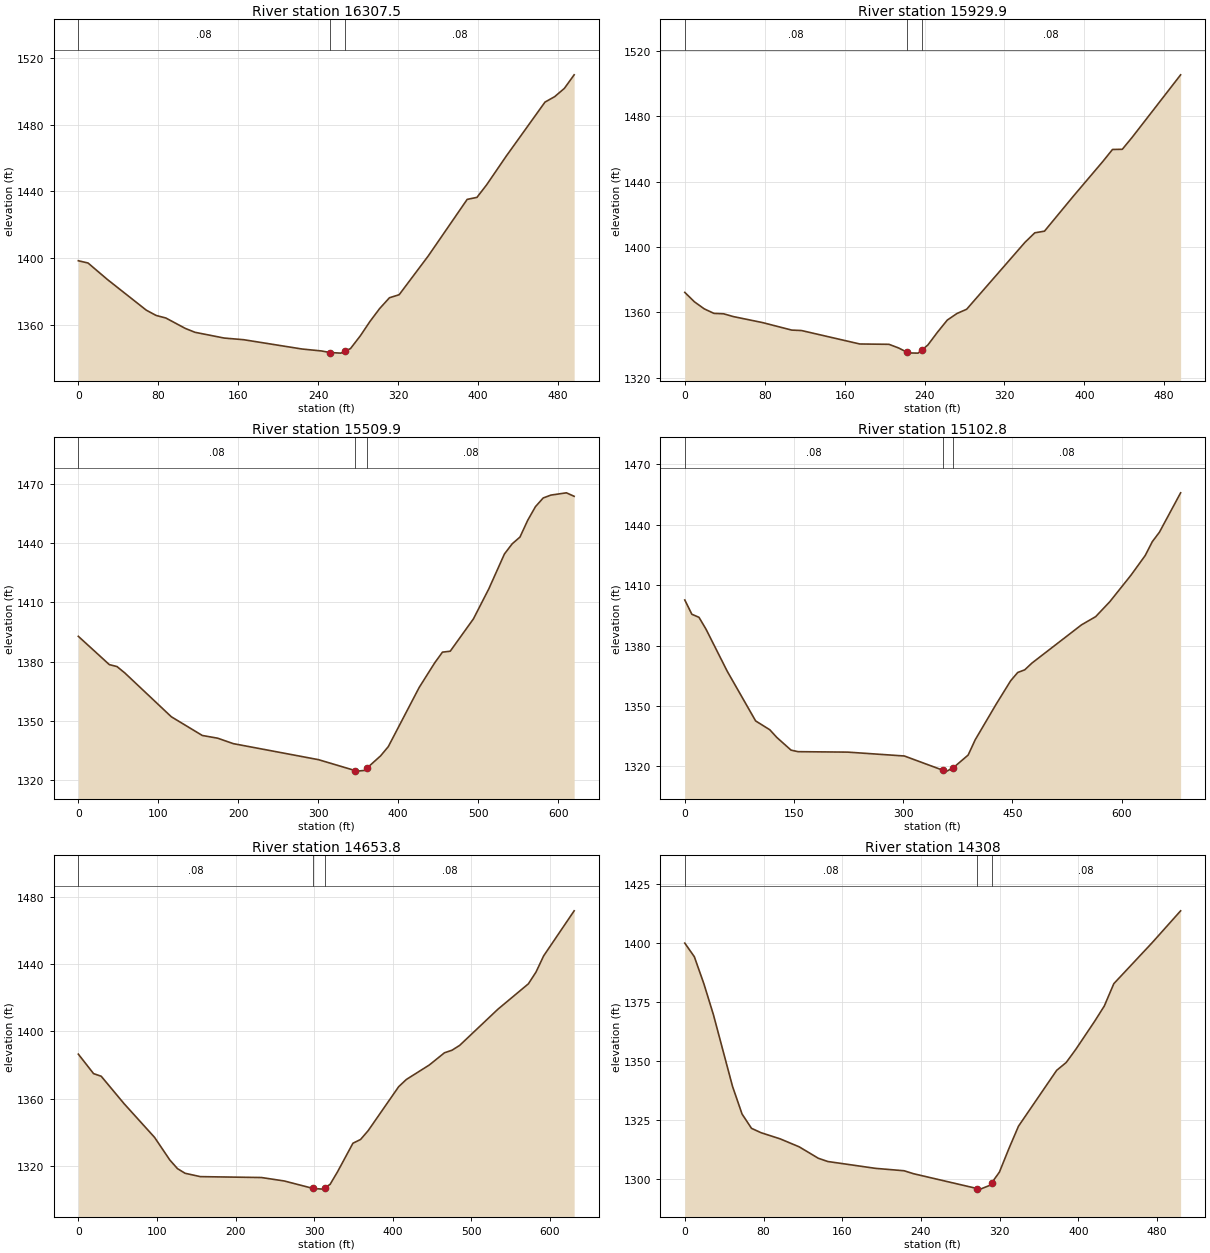
Type RM Length L Ch R = 1 ,16307.5 ,378,377.3,376.6
XS GIS Cut Line= 2
      1747447.11      282353.922      1747342.27       282839.11
#Sta/Elev= 30
       0 1398.45     9.7  1397.1    29.2 1387.16    68.1 1368.79    77.9 1365.64
    87.6 1364.12   107.1 1357.87   116.8 1355.54     146 1352.09   165.5  1351.1
   223.9 1345.52   243.3 1344.36   251.8 1343.42   262.8 1343.05   266.8 1344.18
   272.5  1345.8   282.3  1353.4     292 1362.07   301.7  1369.8   311.5 1376.26
   321.2 1378.08   350.4 1401.38   389.3 1435.25   399.1 1436.46   408.8    1444
   428.2 1461.01   467.2 1493.58   476.9 1496.85   486.6 1501.81   496.4 1509.94
#Mann= 3 , 0 , 0
       0     .08       0   251.8    .045       0   266.8     .08       0
Bank Sta=251.8,266.8
XS Rating Curve= 0 ,0
Exp/Cntr=0.3,0.1

Type RM Length L Ch R = 1 ,15929.9 ,416.5,419.8,423.1
XS GIS Cut Line= 2
     1747071.644      282294.001     1746982.885      282782.365
#Sta/Elev= 30
       0 1372.23     9.7 1366.44    19.5 1362.15    29.2 1359.39    38.9 1359.14
    48.7 1357.42    77.9 1353.76   107.1 1349.17   116.8 1348.91   175.2 1340.68
   204.4 1340.48   214.1 1338.23   222.4 1335.65   223.8 1335.21   233.6 1335.09
   237.4 1337.03   243.3 1340.03     253 1347.91   262.8  1355.3   272.5 1359.33
   282.2 1361.93   340.6 1402.86   350.4 1408.66   360.1 1409.67   389.3 1431.27
   418.5 1452.27   428.2 1459.63     438 1459.73   447.7 1466.91   496.4 1505.27
#Mann= 3 , 0 , 0
       0     .08       0   222.4    .045       0   237.4     .08       0
Bank Sta=222.4,237.4
XS Rating Curve= 0 ,0
Exp/Cntr=0.3,0.1

Type RM Length L Ch R = 1 ,15509.9 ,402.6,407,411.4
XS GIS Cut Line= 2
     1746733.991      282107.403     1746534.988      282694.705
#Sta/Elev= 30
       0 1392.78    38.8 1378.45    48.4 1377.46    58.1 1374.25   116.3 1352.05
     155 1342.58   174.4 1341.18   193.8 1338.44   300.4 1330.32   346.5 1324.76
   348.8 1324.52   358.5  1324.9   361.5 1326.25   377.9  1332.2   387.6 1336.89
   426.3  1366.9   445.7 1379.35   455.4 1384.77   465.1 1385.24   494.1  1401.6
   513.5 1416.93   532.9 1434.47   542.6 1439.62   552.3 1443.02     562 1451.52
   571.7 1458.43   581.4 1462.84     591 1464.29   610.4 1465.44   620.1 1463.68
#Mann= 3 , 0 , 0
       0     .08       0   346.5    .045       0   361.5     .08       0
Bank Sta=346.5,361.5
XS Rating Curve= 0 ,0
Exp/Cntr=0.3,0.1

Type RM Length L Ch R = 1 ,15102.8 ,441.6,448.5,455.6
XS GIS Cut Line= 2
     1746446.058      281959.021     1746100.304      282545.998
#Sta/Elev= 30
       0 1402.63     9.7 1395.54    19.5 1394.01    29.2 1388.08    58.4 1367.14
    97.3 1342.52   116.8 1338.11   126.5 1334.27     146 1327.98   155.7 1327.22
   223.8    1327   301.7 1325.07   354.1 1318.06   360.1 1317.55   369.1 1319.31
   389.3 1325.54     399 1333.14   428.2 1351.08   447.7 1362.47   457.4 1366.59
   467.1 1367.92   476.9 1371.26     545 1390.26   564.5 1394.35   583.9 1401.77
   613.1    1415   632.6 1424.77   642.3 1431.63     652 1436.28   681.2  1455.9
#Mann= 3 , 0 , 0
       0     .08       0   354.1    .045       0   369.1     .08       0
Bank Sta=354.1,369.1
XS Rating Curve= 0 ,0
Exp/Cntr=0.3,0.1

Type RM Length L Ch R = 1 ,14653.8 ,340.6,345.7,350.7
XS GIS Cut Line= 2
     1746145.552      281782.169     1745680.636      282208.339
#Sta/Elev= 30
       0 1386.48    19.4 1374.87    29.1 1373.32    58.2 1356.98      97  1336.9
   116.4 1323.44   126.1 1318.31   135.8 1315.54   155.2 1313.54   232.9 1313.01
     262 1310.95   298.6 1306.51   310.5  1306.1   313.6 1306.99   320.2  1308.9
   329.9 1316.59   349.3 1333.43     359 1335.66   368.7 1340.93   407.5 1367.11
   417.2 1371.38   446.3 1379.97   465.7 1387.28   475.4 1388.83   485.1 1391.71
   533.7 1413.23   572.5 1428.36   582.2 1435.38   591.9    1445   630.7 1471.82
#Mann= 3 , 0 , 0
       0     .08       0   298.6    .045       0   313.6     .08       0
Bank Sta=298.6,313.6
XS Rating Curve= 0 ,0
Exp/Cntr=0.3,0.1

Type RM Length L Ch R = 1 ,14308   ,394.6,396.4,398.3
XS GIS Cut Line= 2
     1745964.834      281588.065     1745524.416      281833.089
#Sta/Elev= 30
       0 1399.86     9.7  1394.1    19.4 1382.67    29.1 1369.58    48.5 1339.28
    58.2 1327.56    67.8 1321.51    77.5 1319.66    96.9 1317.06   116.3 1313.68
   135.7 1308.85   145.4 1307.47   193.8 1304.58   222.9 1303.56   232.6  1302.3
   297.2 1296.03   300.4 1295.79   310.2 1297.41   312.2 1298.57   319.8 1302.99
   329.5 1312.99   339.2 1322.42     378 1346.04   387.7 1349.36   397.4 1354.89
   416.8 1366.92   426.4 1373.24   436.1 1382.71   474.9 1399.96     504 1413.52
#Mann= 3 , 0 , 0
       0     .08       0   297.2    .045       0   312.2     .08       0
Bank Sta=297.2,312.2
XS Rating Curve= 0 ,0
Exp/Cntr=0.3,0.1

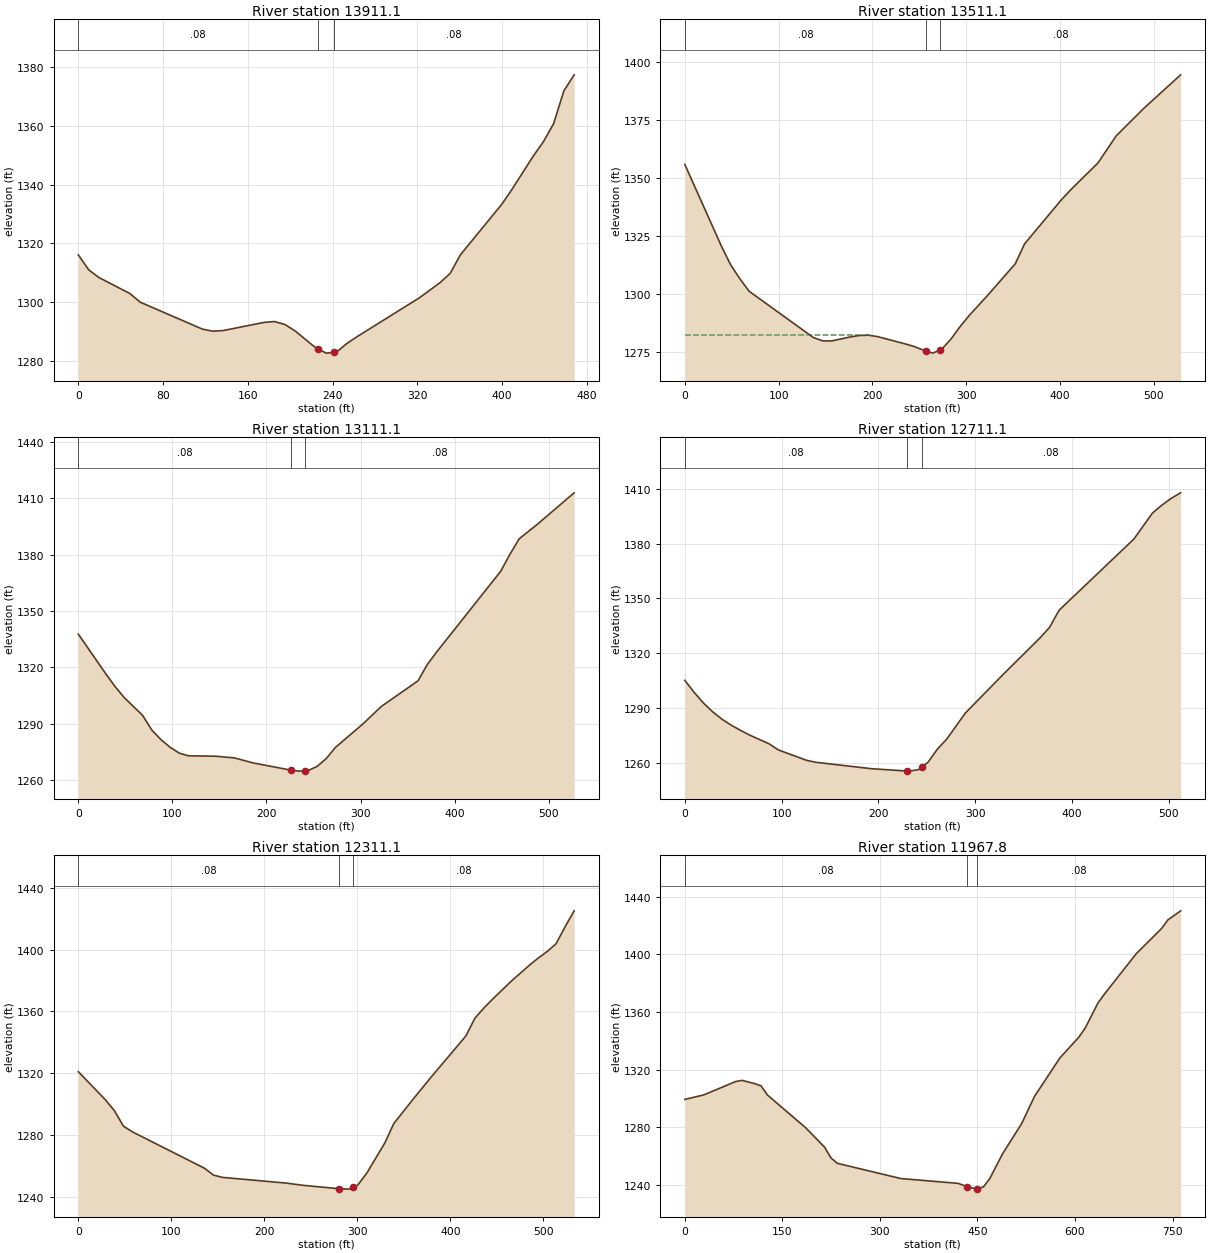
Type RM Length L Ch R = 1 ,13911.1 ,396.2,399.9,403.6
XS GIS Cut Line= 2
     1745773.831      281269.514     1745347.851      281463.142
#Sta/Elev= 30
       0 1316.01     9.8 1310.91    19.5 1308.27    48.7 1302.83    58.5 1299.87
     117 1290.72   126.7    1290   136.5  1290.2   175.5 1293.01   185.2 1293.29
     195 1292.28   204.7 1290.06   224.2 1284.27     226 1283.95     234 1282.52
     241 1282.79   243.7 1282.89   253.5 1285.83   263.2 1288.16   321.7 1301.34
   341.2 1306.51   350.9 1309.69   360.7  1316.1   399.7 1333.31   409.4 1338.43
   428.9 1349.47   438.7 1354.48   448.4 1360.64   458.2 1371.91   467.9 1377.39
#Mann= 3 , 0 , 0
       0     .08       0     226    .045       0     241     .08       0
Bank Sta=226,241
XS Rating Curve= 0 ,0
Exp/Cntr=0.3,0.1

Type RM Length L Ch R = 1 ,13511.1 ,399.7,400,400.2
XS GIS Cut Line= 2
     1745667.843      280927.324     1745157.551      281064.418
#Sta/Elev= 30
       0 1355.88    39.1 1320.48    48.9 1312.48    58.7 1306.46    68.5  1301.1
     137 1281.07   146.8 1279.66   156.6 1279.61   176.1 1281.32   185.9 1281.94
   195.7  1282.1   205.5 1281.47   234.8 1278.34   244.6 1277.18     257 1275.21
   264.2 1274.34     272 1275.73     274 1276.09   283.8  1280.5   293.6 1285.92
   303.3 1290.68   322.9 1299.38   352.3 1312.99     362 1321.48   401.2 1340.54
     411 1344.79   440.3  1356.5   459.9 1368.28   489.2  1380.1   528.4 1394.58
#Mann= 3 , 0 , 0
       0     .08       0     257    .045       0     272     .08       0
#XS Ineff= 2 , 0
          197.94 1282.11
Permanent Ineff=
       F       F
Bank Sta=257,272
XS Rating Curve= 0 ,0
Exp/Cntr=0.3,0.1

Type RM Length L Ch R = 1 ,13111.1 ,401.4,400,398.5
XS GIS Cut Line= 2
      1745550.62      280548.863     1745039.989      280679.709
#Sta/Elev= 30
       0 1337.72    29.3 1316.55      39 1309.85    48.8 1303.96    68.3 1294.52
    78.1 1286.69    87.8 1281.63    97.6 1277.51   107.4 1274.36   117.1 1272.98
   146.4 1272.74     166 1271.85   185.5 1269.22   225.8 1265.37   234.3 1264.82
   240.8 1264.98     244 1265.06   253.8 1267.32   263.6 1271.53   273.3 1277.44
   302.6 1289.96   322.1 1299.22   361.2 1312.92   370.9 1321.49   380.7 1328.07
     449 1371.17   458.8 1380.17   468.6 1388.41   488.1 1396.23   527.1 1412.92
#Mann= 3 , 0 , 0
       0     .08       0   225.8    .045       0   240.8     .08       0
Bank Sta=225.8,240.8
XS Rating Curve= 0 ,0
Exp/Cntr=0.3,0.1

Type RM Length L Ch R = 1 ,12711.1 ,397,399.9,402.8
XS GIS Cut Line= 2
     1745428.586      280154.865     1744941.207      280312.804
#Sta/Elev= 30
       0 1305.13     9.7 1298.52    19.3  1292.7      29 1287.81    38.7 1283.74
    48.3 1280.49      58 1277.62    67.7 1274.98      87 1270.41    96.7 1267.03
   125.7 1261.36   135.3 1260.27   193.3 1256.73   229.9 1255.47     232 1255.42
   241.7 1256.23   244.9 1257.58   251.3 1260.29     261 1267.46   270.7    1273
     290  1287.3   328.7 1308.24   367.3 1328.51     377 1334.23   386.7  1343.5
     464 1382.49   483.3 1396.79     493 1401.11   502.7 1404.84   512.3 1407.81
#Mann= 3 , 0 , 0
       0     .08       0   229.9    .045       0   244.9     .08       0
Bank Sta=229.9,244.9
XS Rating Curve= 0 ,0
Exp/Cntr=0.3,0.1

Type RM Length L Ch R = 1 ,12311.1 ,349.2,343.2,337.3
XS GIS Cut Line= 2
      1745353.75      279800.736      1744829.51      279897.931
#Sta/Elev= 30
       0 1321.02    29.1 1302.85    38.8 1295.77    48.5  1285.8    58.2 1282.07
   135.7 1258.52   145.4 1254.06   155.1  1252.6     223 1248.95   242.4 1247.43
     280 1245.29   290.8 1245.01     295 1246.15   300.5 1247.64   310.2 1255.39
   329.6 1274.88   339.3 1287.48   358.7 1302.24   378.1 1316.59   416.8 1344.18
   426.5  1355.7   436.2 1362.27   445.9 1368.22   465.3 1379.47   484.7 1389.78
   494.4 1394.48   504.1 1398.78   513.8 1403.88   523.5 1414.88   533.2 1425.16
#Mann= 3 , 0 , 0
       0     .08       0     280    .045       0     295     .08       0
Bank Sta=280,295
XS Rating Curve= 0 ,0
Exp/Cntr=0.3,0.1

Type RM Length L Ch R = 1 ,11967.8 ,462.5,456.6,450.7
XS GIS Cut Line= 2
     1745384.668      279333.329     1744697.744      279664.021
#Sta/Elev= 30
       0 1299.44    29.3 1302.57    78.2 1311.84      88 1312.65   107.5  1310.4
   117.3 1308.85   127.1 1302.48   185.7 1279.86     215 1266.29   224.8 1258.82
   234.6  1255.1   332.3 1244.54   420.3 1241.21     434 1238.94     449 1237.25
   449.6 1237.21   459.4 1238.84   469.2 1244.73   488.7 1261.79     518 1282.68
   537.6 1301.45   576.7 1328.15     606 1342.67   615.8 1349.02   635.3 1366.31
   645.1 1372.39     694 1400.42   733.1 1417.98   742.8 1423.93   762.4 1430.25
#Mann= 3 , 0 , 0
       0     .08       0     434    .045       0     449     .08       0
Bank Sta=434,449
XS Rating Curve= 0 ,0
Exp/Cntr=0.3,0.1

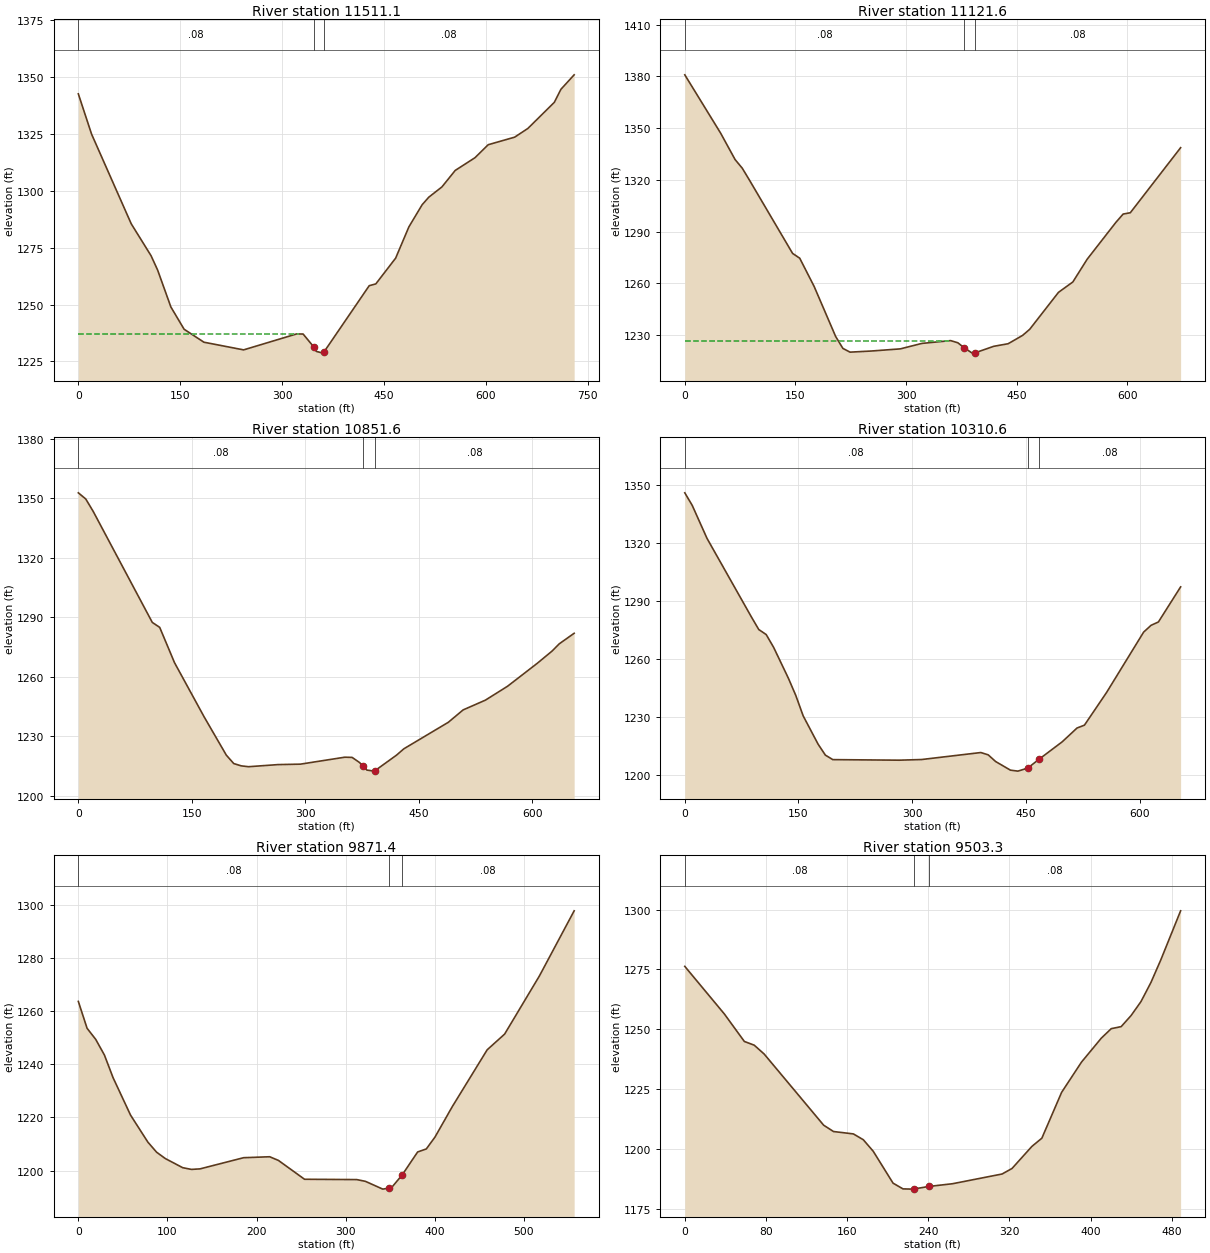
Type RM Length L Ch R = 1 ,11511.1 ,396.7,389.5,382.3
XS GIS Cut Line= 2
     1745042.721      278900.867     1744488.381      279376.147
#Sta/Elev= 30
       0  1342.7    19.5    1325    77.9 1285.55   107.1 1271.51   116.8 1265.18
   136.3 1248.95   155.8 1239.15     185 1233.45   243.4 1230.08   321.3 1237.08
     331 1237.06   346.8 1231.35   350.5 1229.41   360.2 1228.65   361.8 1229.17
   428.4 1258.32   438.1  1259.1   467.3 1270.43   486.8 1284.18   506.3 1293.91
     516 1297.22   535.5 1301.78     555 1309.01   584.2 1314.63   603.6 1320.33
   642.6 1323.66     662 1327.48     701 1338.98   710.7 1344.71   730.2 1351.08
#Mann= 3 , 0 , 0
       0     .08       0   346.8    .045       0   361.8     .08       0
#XS Ineff= 2 , 0
          325.32 1237.11
Permanent Ineff=
       F       F
Bank Sta=346.8,361.8
XS Rating Curve= 0 ,0
Exp/Cntr=0.3,0.1

Type RM Length L Ch R = 1 ,11121.6 ,265.1,270,274.8
XS GIS Cut Line= 2
     1744666.194      278566.998     1744317.957      279141.814
#Sta/Elev= 30
       0 1380.95    48.7 1347.03    68.2 1331.78    77.9 1326.77    87.7 1319.83
   146.1 1277.36   155.8 1274.56   175.3 1258.21   204.5 1229.15   214.3 1222.24
     224 1220.07   253.2 1220.73   292.2 1221.97   321.4 1225.14   360.4 1226.76
   370.1 1225.51   378.5 1222.67   389.6  1219.5   393.5 1219.68   418.8 1223.46
   438.3 1224.95   457.8 1229.76   467.5 1233.31   506.5 1254.74     526 1260.78
   545.4 1273.96   584.4 1295.39   594.2 1300.18   603.9 1300.94   672.1 1338.68
#Mann= 3 , 0 , 0
       0     .08       0   378.5    .045       0   393.5     .08       0
#XS Ineff= 2 , 0
          358.42 1226.69
Permanent Ineff=
       F       F
Bank Sta=378.5,393.5
XS Rating Curve= 0 ,0
Exp/Cntr=0.3,0.1

Type RM Length L Ch R = 1 ,10851.6 ,541.4,540.7,540
XS GIS Cut Line= 2
     1744516.964      278455.075     1744065.423       278930.38
#Sta/Elev= 30
       0 1352.82     9.8 1349.72    19.6 1343.48    97.8 1287.39   107.6 1284.89
   127.2 1267.05   166.3 1239.74   195.7 1220.37   205.5 1216.13   215.3 1214.98
     225 1214.54   264.2 1215.61   293.6 1215.83   352.3 1219.34     362 1219.24
   371.8 1216.66   376.9 1214.67   381.6 1212.83   391.4 1212.31   391.9 1212.44
   420.8  1220.4   430.5  1223.6   489.2 1236.96   508.8 1243.22   538.2 1248.14
   567.5 1255.15   606.7 1266.71   626.2 1272.86     636 1276.61   655.6 1281.91
#Mann= 3 , 0 , 0
       0     .08       0   376.9    .045       0   391.9     .08       0
#XS Ineff= 2 , 0
          357.62 1219.25
Permanent Ineff=
       F       F
Bank Sta=376.9,391.9
XS Rating Curve= 0 ,0
Exp/Cntr=0.3,0.1

Type RM Length L Ch R = 1 ,10310.6 ,441,438.9,436.6
XS GIS Cut Line= 2
     1744135.942      278196.974     1743687.001      278672.843
#Sta/Elev= 30
       0  1345.8     9.8 1339.32    29.3 1322.29    87.9 1281.69    97.6 1275.21
   107.4 1272.62   117.2 1266.01   136.7 1250.05   146.5 1241.13   156.2 1230.62
   175.8 1216.08   185.5 1210.36   195.3 1208.04   283.2 1207.75   312.5 1208.09
   390.6  1211.7   400.3 1210.51   410.1 1207.06   429.6 1202.61   439.4  1202.1
   452.3 1203.63   467.3  1208.2     498 1217.25   517.5 1224.35   527.3 1225.84
   556.6 1242.77   605.4 1273.88   615.2 1277.39   624.9 1279.12   654.2 1297.23
#Mann= 3 , 0 , 0
       0     .08       0   452.3    .045       0   467.3     .08       0
#XS Ineff= 2 , 0
          389.69 1211.43
Permanent Ineff=
       F       F
Bank Sta=452.3,467.3
XS Rating Curve= 0 ,0
Exp/Cntr=0.3,0.1

Type RM Length L Ch R = 1 ,9871.4  ,368.5,367.9,367.3
XS GIS Cut Line= 2
     1743688.412      278000.865     1743378.926      278463.181
#Sta/Elev= 30
       0 1263.64     9.8 1253.54    19.5 1249.36    29.3 1243.45      39 1234.93
    58.6 1220.86    78.1 1210.67    87.8 1206.92    97.6 1204.52   117.1 1201.09
   126.9 1200.44   136.6 1200.64   185.4 1204.84   214.7  1205.2   224.5 1203.82
   253.8 1196.73   312.3 1196.61   322.1 1195.95   341.6 1193.02   348.3  1193.4
   351.4 1193.58   363.3 1198.34   380.7    1207   390.4 1208.13   400.2 1212.63
   419.7 1224.13   458.7 1245.43   478.3 1251.35   517.3 1273.21   556.3 1297.72
#Mann= 3 , 0 , 0
       0     .08       0   348.3    .045       0   363.3     .08       0
Bank Sta=348.3,363.3
XS Rating Curve= 0 ,0
Exp/Cntr=0.3,0.1

Type RM Length L Ch R = 1 ,9503.3  ,390.5,385,379.4
XS GIS Cut Line= 2
     1743349.551      277852.375     1743090.824      278267.111
#Sta/Elev= 30
       0 1276.28    39.1 1256.34    58.7  1244.9    68.4 1243.35    78.2 1239.66
   136.9 1209.89   146.6 1207.25   166.2 1206.25     176 1203.81   185.8 1198.98
   205.3 1185.67   215.1 1183.27   224.9 1183.17   225.8 1183.23   240.8  1184.3
     264 1185.43   312.8 1189.49   322.6 1191.81   342.2 1201.03     352 1204.46
   371.5 1223.64   391.1 1236.28   410.6 1246.27   420.4 1250.24   430.2  1251.1
   439.9 1255.69   449.7 1261.55   459.5 1269.52   469.3 1279.03   488.8  1299.5
#Mann= 3 , 0 , 0
       0     .08       0   225.8    .045       0   240.8     .08       0
Bank Sta=225.8,240.8
XS Rating Curve= 0 ,0
Exp/Cntr=0.3,0.1