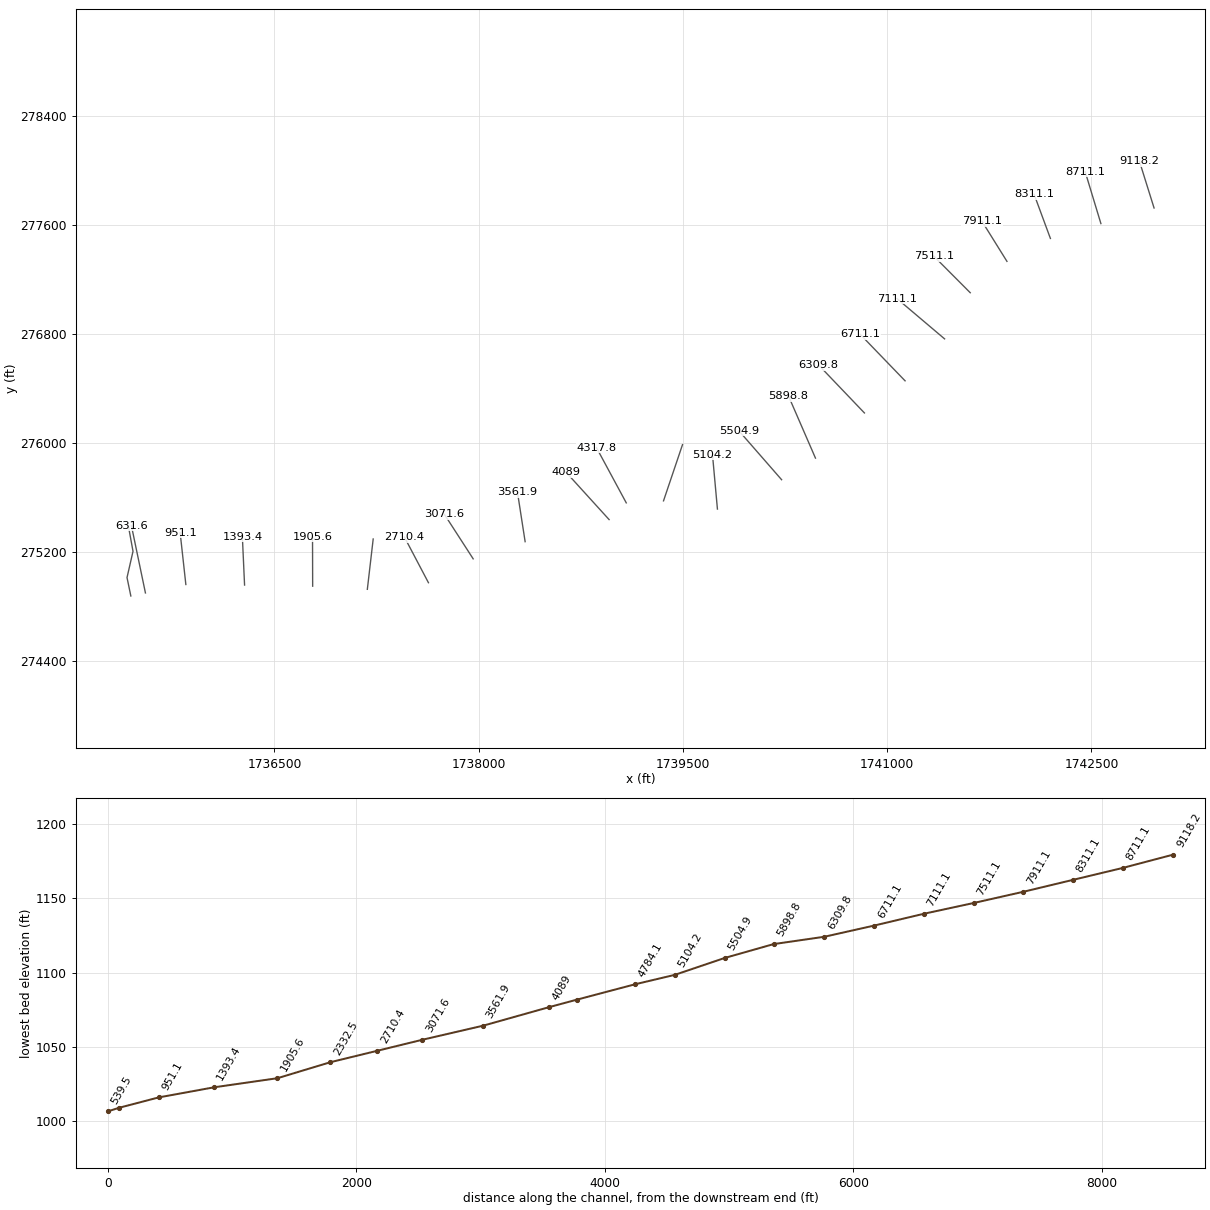
HEC-RAS study RIGHTBFLCK.prj: RIGHTBFLCK

--- RIGHTBFLCK.g01 (geometry) --- (continued)

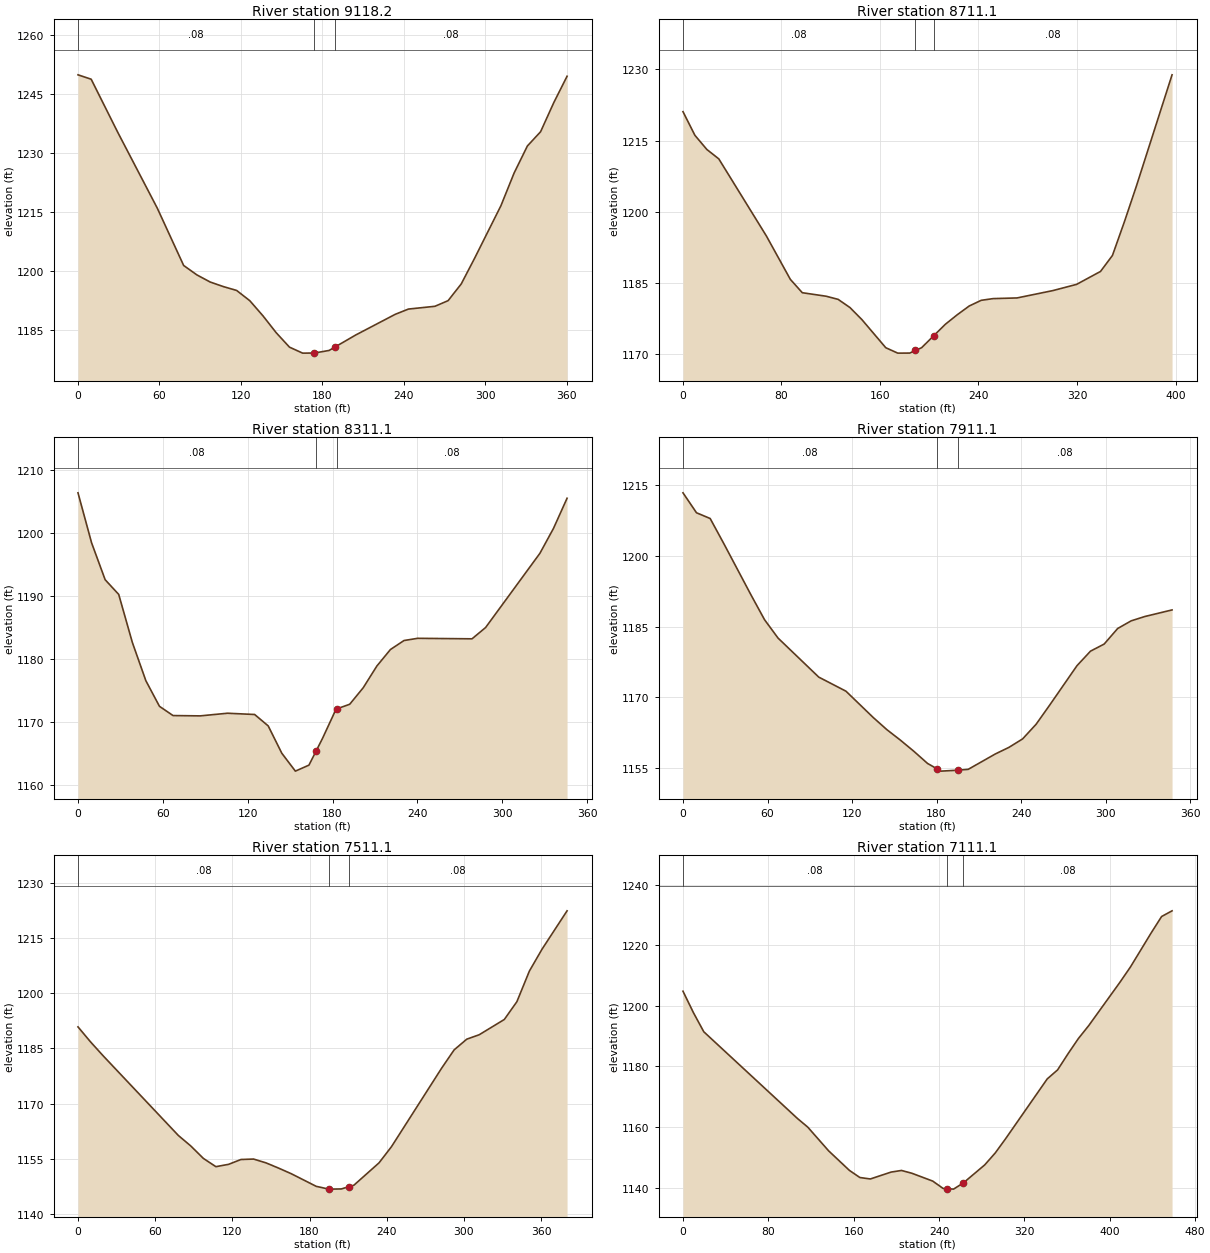
Type RM Length L Ch R = 1 ,9118.2  ,407.3,407,406.7
XS GIS Cut Line= 2
     1742959.641      277727.079     1742852.128      278070.716
#Sta/Elev= 30
       0 1249.78     9.7 1248.67    29.2 1235.26    58.4 1215.97    77.8 1201.45
    87.6 1199.05    97.3 1197.26     107  1196.1   116.8 1195.12   126.5 1192.52
   136.2 1188.68     146 1184.38   155.7 1180.75   165.4 1179.23   173.9 1179.25
   184.9 1179.91   188.9 1180.71   204.4 1183.81   233.6 1189.07   243.3  1190.4
   262.8  1191.1   272.5 1192.53   282.2 1196.78   291.9  1203.2   311.4  1216.6
   321.1 1224.88   330.9 1231.75   340.6 1235.35   350.3 1242.72   360.1 1249.42
#Mann= 3 , 0 , 0
       0     .08       0   173.9    .045       0   188.9     .08       0
Bank Sta=173.9,188.9
XS Rating Curve= 0 ,0
Exp/Cntr=0.3,0.1

Type RM Length L Ch R = 1 ,8711.1  ,398.6,399.9,401.2
XS GIS Cut Line= 2
     1742569.266      277612.608     1742454.026      277992.737
#Sta/Elev= 30
       0 1221.11     9.7 1216.13    19.4 1213.15    29.1 1211.17    67.8 1194.91
    87.2  1185.8    96.9 1182.99   116.3 1182.25     126 1181.59   135.6 1179.87
   145.3 1177.33   164.7 1171.41   174.4 1170.27   184.1 1170.28   188.8 1170.83
   193.8 1171.41   203.8 1173.97   213.1 1176.35   222.8 1178.36   232.5  1180.2
   242.2 1181.39   251.9 1181.75   271.3 1181.89   300.3 1183.43   319.7 1184.75
   339.1 1187.47   348.8 1190.84   358.5 1197.93   368.2 1205.41   397.2 1228.87
#Mann= 3 , 0 , 0
       0     .08       0   188.8    .045       0   203.8     .08       0
Bank Sta=188.8,203.8
XS Rating Curve= 0 ,0
Exp/Cntr=0.3,0.1

Type RM Length L Ch R = 1 ,8311.1  ,395.4,400,404.6
XS GIS Cut Line= 2
     1742198.456      277503.516     1742078.617        277827.9
#Sta/Elev= 30
       0  1206.4     9.6 1198.48    19.2 1192.62    28.8 1190.29    38.4  1182.7
      48  1176.6    57.6 1172.55    67.2 1171.08    86.4 1171.03   105.7 1171.45
   124.9 1171.25   134.5 1169.44   144.1 1165.11   153.7 1162.27   163.3 1163.22
   168.3 1165.43   172.9 1167.47   182.5 1172.11   183.3 1172.17   192.1 1172.87
   201.7  1175.5   211.3 1178.93   220.9 1181.55   230.5 1182.98   240.2 1183.33
   278.6 1183.25   288.2 1185.04   326.6 1196.81   336.2 1200.76   345.8 1205.54
#Mann= 3 , 0 , 0
       0     .08       0   168.3    .045       0   183.3     .08       0
Bank Sta=168.3,183.3
XS Rating Curve= 0 ,0
Exp/Cntr=0.3,0.1

Type RM Length L Ch R = 1 ,7911.1  ,394.7,399.8,404.9
XS GIS Cut Line= 2
     1741879.382      277335.213     1741695.762      277629.858
#Sta/Elev= 30
       0 1213.43     9.6 1209.19    19.3 1207.97    28.9 1202.68    48.2 1191.77
    57.9 1186.45    67.5 1182.54    96.4 1174.24   115.7 1171.25     135 1165.67
   144.7 1163.08   154.3 1160.85   163.9 1158.47   173.6 1155.89   180.3 1154.75
   183.2 1154.25   195.3 1154.45   202.5 1154.63   221.8 1157.91   231.4  1159.3
   241.1  1161.1   250.7 1164.22   260.4 1168.32   279.7 1176.67   289.3 1179.76
     299 1181.27   308.6 1184.58   318.2 1186.21   327.9 1187.13   347.2 1188.53
#Mann= 3 , 0 , 0
       0     .08       0   180.3    .045       0   195.3     .08       0
Bank Sta=180.3,195.3
XS Rating Curve= 0 ,0
Exp/Cntr=0.3,0.1

Type RM Length L Ch R = 1 ,7511.1  ,398.1,400,402
XS GIS Cut Line= 2
     1741609.809      277104.925     1741341.458      277374.221
#Sta/Elev= 30
       0 1190.86     9.8 1186.76    19.5 1183.01      78 1161.32    87.7 1158.45
    97.5 1155.06   107.2 1152.82     117 1153.45   126.7 1154.77   136.5 1154.89
   146.2 1153.85     156 1152.42   165.7 1150.92   185.2 1147.47     195 1146.71
   195.4 1146.71   204.7 1146.76   210.4 1147.35   214.5 1147.78     234 1153.85
   243.7 1158.26   282.7 1179.63   292.4  1184.6   302.2 1187.51   311.9 1188.72
   331.4 1192.87   341.2 1197.72   350.9 1206.04   360.7 1211.98   380.2 1222.44
#Mann= 3 , 0 , 0
       0     .08       0   195.4    .045       0   210.4     .08       0
Bank Sta=195.4,210.4
XS Rating Curve= 0 ,0
Exp/Cntr=0.3,0.1

Type RM Length L Ch R = 1 ,7111.1  ,402.2,399.9,397.7
XS GIS Cut Line= 2
     1741421.458      276765.999     1741071.529      277062.094
#Sta/Elev= 30
       0  1204.8     9.8 1197.72    19.5 1191.42   107.3  1162.8     117 1159.94
   136.5 1152.13     156 1145.67   165.8 1143.32   175.6 1142.84   195.1 1145.12
   204.8 1145.65   214.6 1144.72   234.1 1142.14   243.8 1139.72   247.9 1139.62
   253.6 1139.49   262.9 1141.57   282.8 1147.48   292.6 1151.39   302.3 1156.08
   341.4 1175.86   351.1 1178.83   360.9 1184.16   370.6 1189.18   380.4  1193.5
   409.6 1207.78   419.4  1212.8   438.9 1224.08   448.6 1229.45   458.4 1231.33
#Mann= 3 , 0 , 0
       0     .08       0   247.9    .045       0   262.9     .08       0
#XS Ineff= 2 , 0
          205.04 1145.49
Permanent Ineff=
       F       F
Bank Sta=247.9,262.9
XS Rating Curve= 0 ,0
Exp/Cntr=0.3,0.1

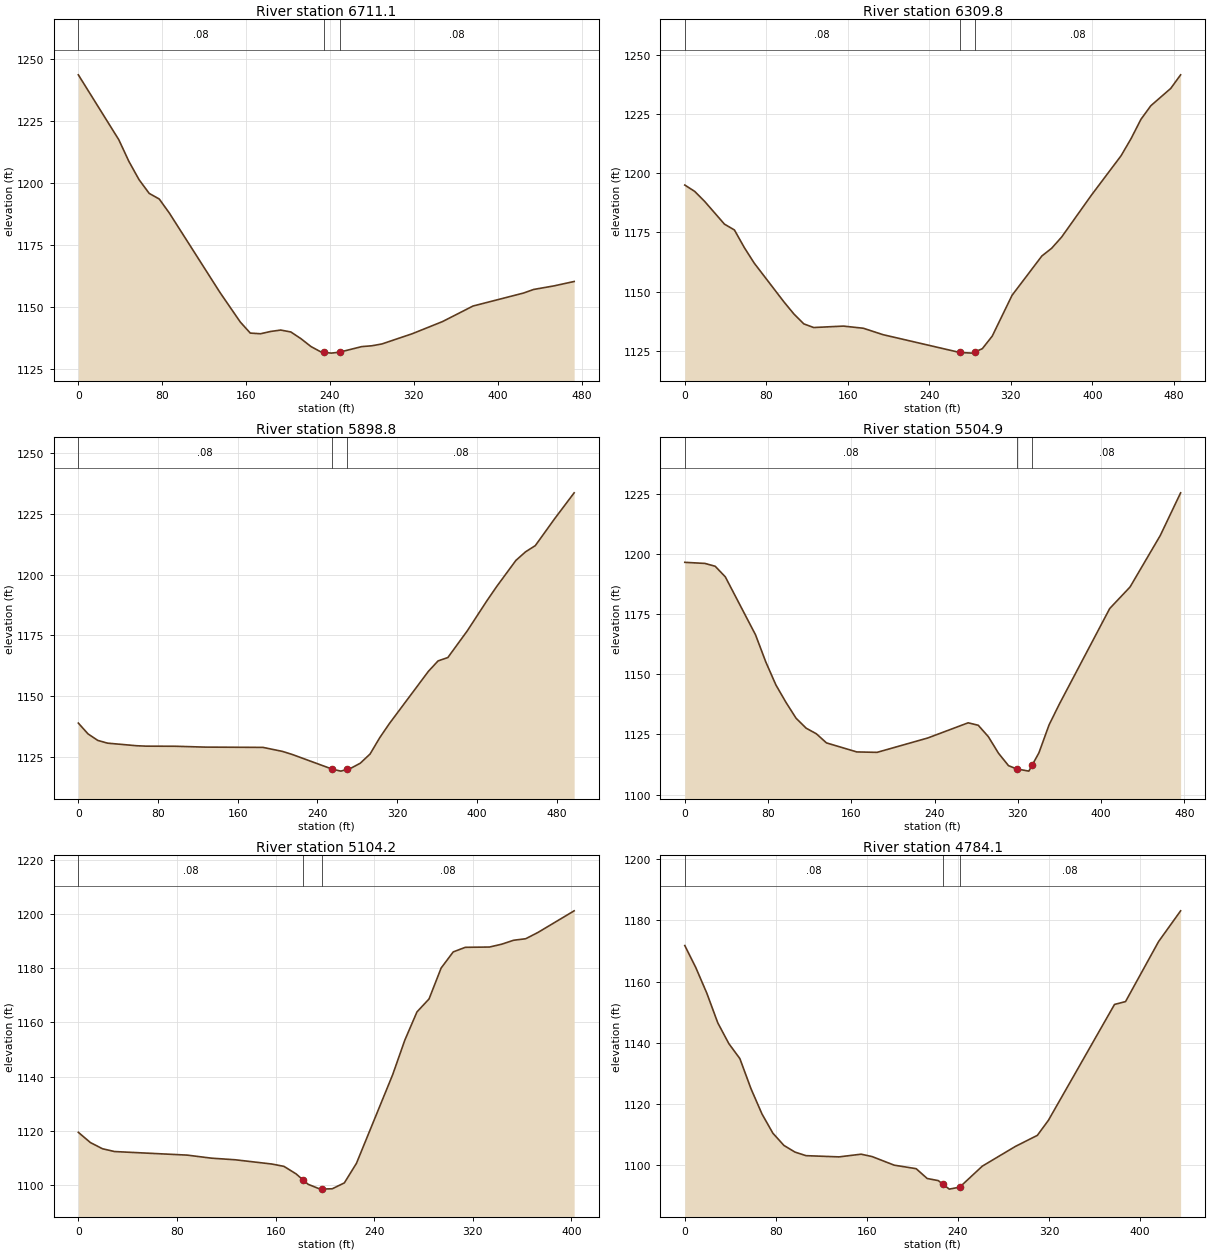
Type RM Length L Ch R = 1 ,6711.1  ,401.6,401.1,399.8
XS GIS Cut Line= 2
      1741131.18      276458.048     1740802.839      276798.329
#Sta/Elev= 30
       0 1243.75    38.6 1217.59    48.2 1208.88    57.9 1201.49    67.6 1195.95
    77.2 1193.68    86.8 1188.03   135.1 1156.01   154.4 1144.14     164 1139.64
   173.7 1139.37   183.4 1140.29     193 1140.86   202.7 1140.09   212.3 1137.39
     222 1134.18   231.6    1132   234.3 1131.88   241.3 1131.56   249.3 1131.96
   270.2 1134.18   279.9 1134.52   289.5 1135.25   318.5 1139.38   347.4 1144.29
   376.4 1150.54   424.6 1155.78   434.3 1157.23   453.6 1158.66   472.9 1160.44
#Mann= 3 , 0 , 0
       0     .08       0   234.3    .045       0   249.3     .08       0
Bank Sta=234.3,249.3
XS Rating Curve= 0 ,0
Exp/Cntr=0.3,0.1

Type RM Length L Ch R = 1 ,6309.8  ,417.3,409.8,403.1
XS GIS Cut Line= 2
     1740832.774      276222.056     1740496.546      276573.854
#Sta/Elev= 30
       0 1195.04     9.7 1192.36    19.5 1188.12    38.9 1178.53    48.7 1176.06
    58.4 1168.64    68.1 1162.08    97.3 1145.68   107.1 1140.56   116.8 1136.39
   126.5 1134.85   155.7 1135.46   175.2 1134.55   194.6 1131.83   269.8 1124.32
   282.2 1124.04   284.8 1124.54     292 1125.92   301.7 1131.21   321.2 1148.48
   350.4 1165.06   360.1 1168.36   369.8 1173.05     399 1190.73   428.2 1207.44
     438 1214.67   447.7 1222.83   457.4 1228.55   476.9 1235.85   486.6 1241.59
#Mann= 3 , 0 , 0
       0     .08       0   269.8    .045       0   284.8     .08       0
Bank Sta=269.8,284.8
XS Rating Curve= 0 ,0
Exp/Cntr=0.3,0.1

Type RM Length L Ch R = 1 ,5898.8  ,386.7,393.7,400.7
XS GIS Cut Line= 2
     1740473.203      275890.529     1740274.953      276347.085
#Sta/Elev= 30
       0 1138.88     9.8  1134.4    19.5 1131.75    29.3 1130.61    58.6 1129.54
    68.3 1129.37    97.6 1129.33   126.9 1128.98   185.4 1128.86     205  1127.2
   214.7 1125.95   254.9  1119.9   263.5 1119.08   269.9 1119.82   273.3 1120.22
     283 1122.34   292.8 1126.11   302.6 1132.89   312.3 1138.72   351.4 1160.21
   361.1 1164.51   370.9 1165.89   390.4 1176.88   409.9 1189.16   419.7 1195.03
   439.2 1205.92   448.9 1209.46   458.7 1212.02   478.2 1223.16   497.7 1233.78
#Mann= 3 , 0 , 0
       0     .08       0   254.9    .045       0   269.9     .08       0
Bank Sta=254.9,269.9
XS Rating Curve= 0 ,0
Exp/Cntr=0.3,0.1

Type RM Length L Ch R = 1 ,5504.9  ,414.6,400.5,386.3
XS GIS Cut Line= 2
     1740224.521      275731.921     1739911.299      276090.717
#Sta/Elev= 30
       0 1196.53    19.4 1196.07    29.2 1194.89    38.9 1190.51      68 1166.36
    77.8 1155.14    87.5 1145.59    97.2 1138.33   106.9 1131.74   116.6  1127.6
   126.4 1125.27   136.1 1121.49   165.2 1117.74   184.7 1117.56   233.3 1123.52
   272.2 1129.84   281.9 1128.82   291.6 1124.08   301.3 1117.22     311 1112.02
   318.9 1110.67   330.5 1109.76   333.9 1112.43   340.2 1117.38   349.9 1128.95
   359.6 1137.45   408.2 1177.34   427.7 1186.27   456.8 1207.72   476.3 1225.41
#Mann= 3 , 0 , 0
       0     .08       0   318.9    .045       0   333.9     .08       0
Bank Sta=318.9,333.9
XS Rating Curve= 0 ,0
Exp/Cntr=0.3,0.1

Type RM Length L Ch R = 1 ,5104.2  ,329.5,320.1,310.7
XS GIS Cut Line= 2
     1739753.294      275516.368     1739716.884      275916.894
#Sta/Elev= 30
       0  1119.4     9.8 1115.62    19.6 1113.34    29.4 1112.31    88.3 1110.99
   107.9 1109.87   127.5 1109.26     157  1107.7   166.8 1106.84   176.6 1104.08
   182.5 1101.76   186.4 1100.22   196.2 1098.44   197.5 1098.46     206 1098.57
   215.8 1100.75   225.6 1107.96     255 1140.69   264.8 1153.37   274.7 1163.84
   284.5 1168.63   294.3 1180.03   304.1 1185.98   313.9 1187.67   333.5 1187.78
   343.3 1188.81   353.1 1190.28   362.9 1190.84   372.8 1193.15   402.2 1201.14
#Mann= 3 , 0 , 0
       0     .08       0   182.5    .045       0   197.5     .08       0
Bank Sta=182.5,197.5
XS Rating Curve= 0 ,0
Exp/Cntr=0.3,0.1

Type RM Length L Ch R = 1 ,4784.1  ,447.3,465.9,484.4
XS GIS Cut Line= 2
     1739357.394      275576.569     1739496.897      275989.314
#Sta/Elev= 30
       0 1171.79     9.7 1164.57    19.4 1156.16      29 1146.49    38.7 1139.71
    48.4  1134.8    58.1 1125.01    67.8 1116.71    77.4  1110.4    87.1  1106.4
    96.8 1104.22   106.5 1103.05   135.6 1102.65   154.9 1103.53   164.6 1102.75
     184 1099.94   203.3 1098.79     213 1095.58   222.7 1094.89   226.6 1093.77
   232.4  1092.1   241.6 1092.75   261.4 1099.61   290.5 1106.07   309.8 1109.69
   319.5  1114.6   377.6 1152.52   387.3 1153.46   416.3 1173.07   435.7 1183.15
#Mann= 3 , 0 , 0
       0     .08       0   226.6    .045       0   241.6     .08       0
Bank Sta=226.6,241.6
XS Rating Curve= 0 ,0
Exp/Cntr=0.3,0.1

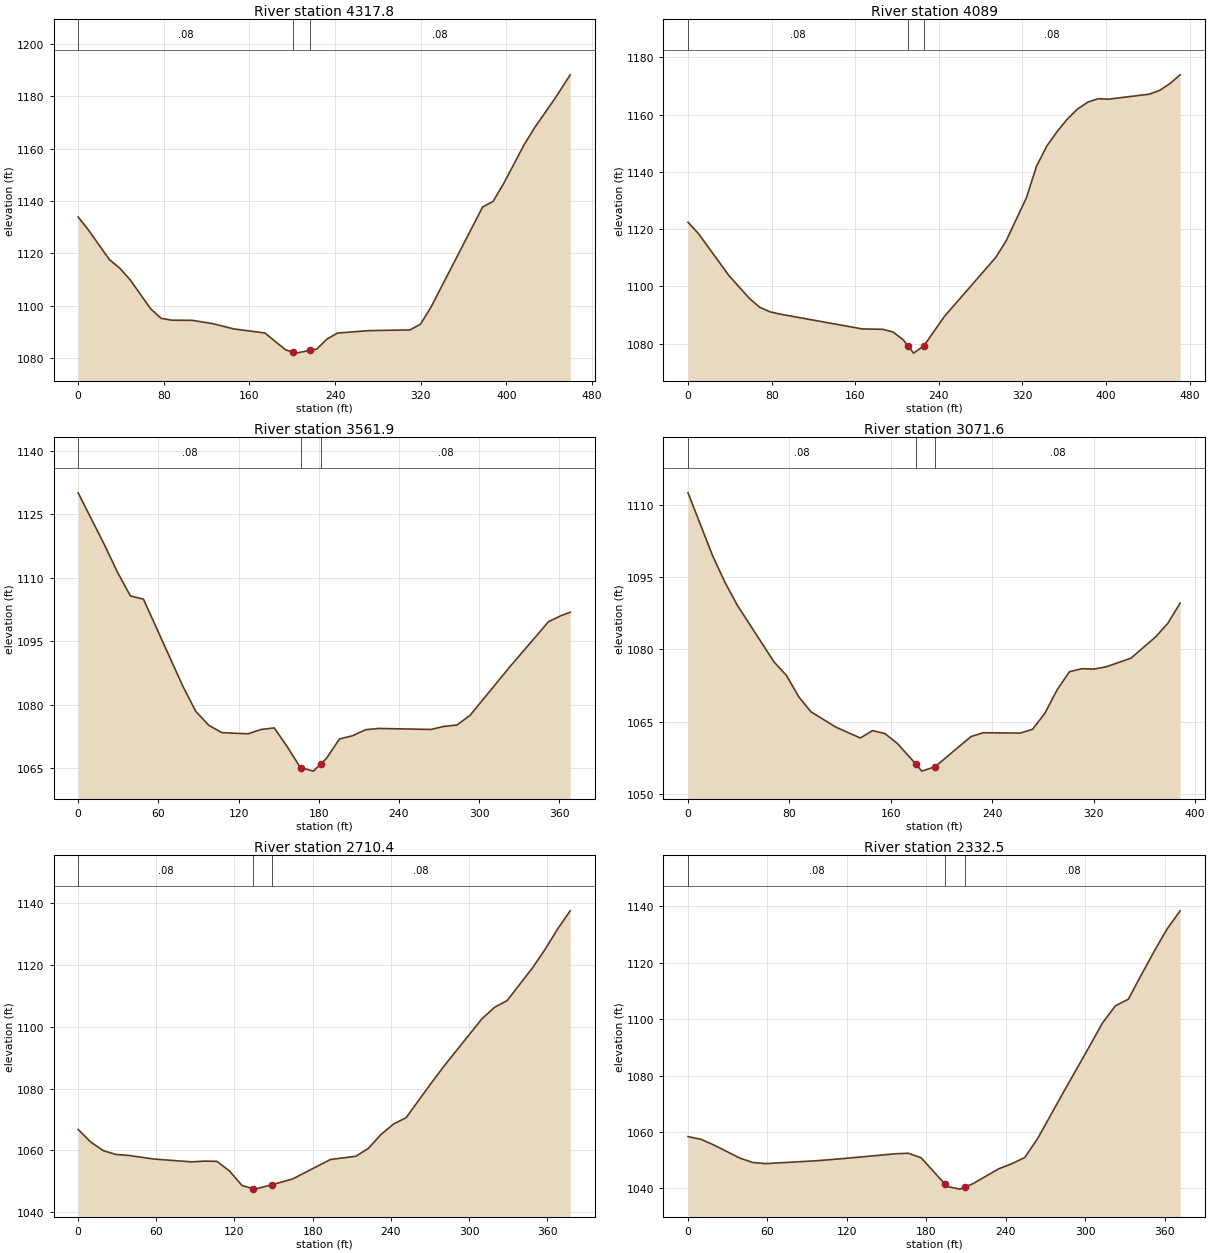
Type RM Length L Ch R = 1 ,4317.8  ,223.4,228.9,234.4
XS GIS Cut Line= 3
     1739083.864      275561.783      1738872.28      275953.969
      1738865.65      275966.258
#Sta/Elev= 30
       0 1133.86     9.7 1128.83    29.1  1117.6    38.8  1114.3    48.4 1109.94
    67.8 1098.73    77.5 1095.12    87.2 1094.41   106.6 1094.35   125.9 1093.08
   145.3 1091.08   174.4 1089.52   193.8 1083.08   201.1 1082.12   203.4 1081.82
   216.1 1082.85   222.8 1083.34   232.5 1087.23   242.2 1089.48   271.2 1090.42
     310 1090.69   319.7 1092.88   329.4 1099.28   377.8 1137.67   387.5 1139.78
   397.2 1146.44   416.6 1161.49   426.2  1167.9   445.6 1179.29   459.6 1188.17
#Mann= 3 , 0 , 0
       0     .08       0   201.1    .045       0   216.1     .08       0
Bank Sta=201.1,216.1
XS Rating Curve= 0 ,0
Exp/Cntr=0.3,0.1

Type RM Length L Ch R = 1 ,4089    ,540.3,527.1,513.9
XS GIS Cut Line= 2
     1738957.766      275439.097     1738641.021      275787.647
#Sta/Elev= 30
       0 1122.37     9.8 1118.52    39.2 1103.74    58.9 1095.71    68.7 1092.68
    78.5 1091.08    88.3 1090.29   166.8 1085.12   186.4 1084.99   196.2 1084.05
     206 1081.31   210.8 1079.06   215.9 1076.67   225.8 1079.24   245.3 1089.44
   294.4 1110.04   304.2 1115.71   323.8 1130.88   333.6 1142.01   343.4 1149.02
   353.2 1154.03     363 1158.42   372.8 1161.94   382.7 1164.36   392.5 1165.54
   402.3 1165.38   441.5 1167.13   451.4 1168.45   461.2 1170.81     471 1173.89
#Mann= 3 , 0 , 0
       0     .08       0   210.8    .045       0   225.8     .08       0
Bank Sta=210.8,225.8
XS Rating Curve= 0 ,0
Exp/Cntr=0.3,0.1

Type RM Length L Ch R = 1 ,3561.9  ,480.8,490.3,499.8
XS GIS Cut Line= 3
     1738341.206      275276.844     1738285.816      275634.338
     1738284.827      275640.717
#Sta/Elev= 30
       0 1130.11    19.6 1117.87    29.3 1111.42    39.1 1105.74    48.9 1104.95
    78.2 1084.48      88 1078.44    97.8 1075.13   107.6  1073.4   127.1 1073.13
   136.9 1074.15   146.7 1074.52   156.4 1070.11   166.2 1065.17   166.5 1065.14
     176  1064.3   181.5 1065.99   185.8 1067.32   195.6 1071.91   205.3 1072.66
   215.1 1074.09   224.9 1074.39     264 1074.16   273.8 1074.88   283.5 1075.21
   293.3 1077.51   322.6 1088.81     352 1099.65   361.8 1101.13   368.2 1101.86
#Mann= 3 , 0 , 0
       0     .08       0   166.5    .045       0   181.5     .08       0
Bank Sta=166.5,181.5
XS Rating Curve= 0 ,0
Exp/Cntr=0.3,0.1

Type RM Length L Ch R = 1 ,3071.6  ,363,360.9,358.8
XS GIS Cut Line= 2
     1737959.699      275150.815     1737748.941      275476.842
#Sta/Elev= 30
       0 1112.42    19.4 1099.39    29.1 1093.91    38.8 1089.19    67.9 1077.39
    77.6 1074.64    87.4 1070.19      97 1067.09   116.5 1063.94   135.9 1061.68
   145.6 1063.21   155.3 1062.59     165 1060.58   179.9 1056.24   184.4 1054.82
   194.9 1055.73   223.2 1061.97   232.9 1062.77     262 1062.69   271.8 1063.48
   281.5  1066.8   291.2 1071.66   300.9 1075.39   310.6 1076.02   320.3 1075.94
     330 1076.42   349.4  1078.2   368.8 1082.58   378.5 1085.42   388.2  1089.6
#Mann= 3 , 0 , 0
       0     .08       0   179.9    .045       0   194.9     .08       0
Bank Sta=179.9,194.9
XS Rating Curve= 0 ,0
Exp/Cntr=0.3,0.1

Type RM Length L Ch R = 1 ,2710.4  ,391.5,378,364.4
XS GIS Cut Line= 2
     1737631.201      274975.577     1737455.209      275309.818
#Sta/Elev= 30
       0 1066.79     9.7  1062.7    19.4  1059.9    29.1 1058.67    38.7 1058.38
    58.1  1057.2    87.2 1056.28    96.9 1056.52   106.5 1056.46   116.2 1053.31
   125.9 1048.59     134 1047.64   135.6 1047.45     149  1048.9   164.7 1050.76
   193.7 1057.06   213.1 1058.09   222.8 1060.66   232.5 1065.18   242.1 1068.54
   251.8 1070.62   271.2 1081.92   280.9 1087.35   309.9 1102.62   319.6 1106.35
   329.3 1108.55   348.7 1119.12   358.4 1125.12   368.1 1131.78   377.7 1137.62
#Mann= 3 , 0 , 0
       0     .08       0     134    .045       0     149     .08       0
Bank Sta=134,149
XS Rating Curve= 0 ,0
Exp/Cntr=0.3,0.1

Type RM Length L Ch R = 1 ,2332.5  ,424.1,426.8,429.5
XS GIS Cut Line= 2
     1737182.494      274927.173     1737225.469      275296.483
#Sta/Elev= 29
       0 1058.38     9.8 1057.43    19.6 1055.38    39.1 1050.78    48.9 1049.21
    58.7  1048.8    97.8 1049.85   117.4  1050.6   156.6 1052.29   166.3 1052.49
   176.1 1050.89     194 1041.61   195.7 1040.72   205.5 1039.76     209 1040.45
   215.2 1041.68   234.8 1046.98   244.6 1048.76   254.4 1050.96   264.2 1057.73
   283.7 1074.16   303.3 1090.38   313.1 1098.64   322.9 1104.77   332.7 1107.11
   342.4 1115.66   352.2 1124.09     362 1132.06   371.8 1138.45
#Mann= 3 , 0 , 0
       0     .08       0     194    .045       0     209     .08       0
Bank Sta=194,209
XS Rating Curve= 0 ,0
Exp/Cntr=0.3,0.1

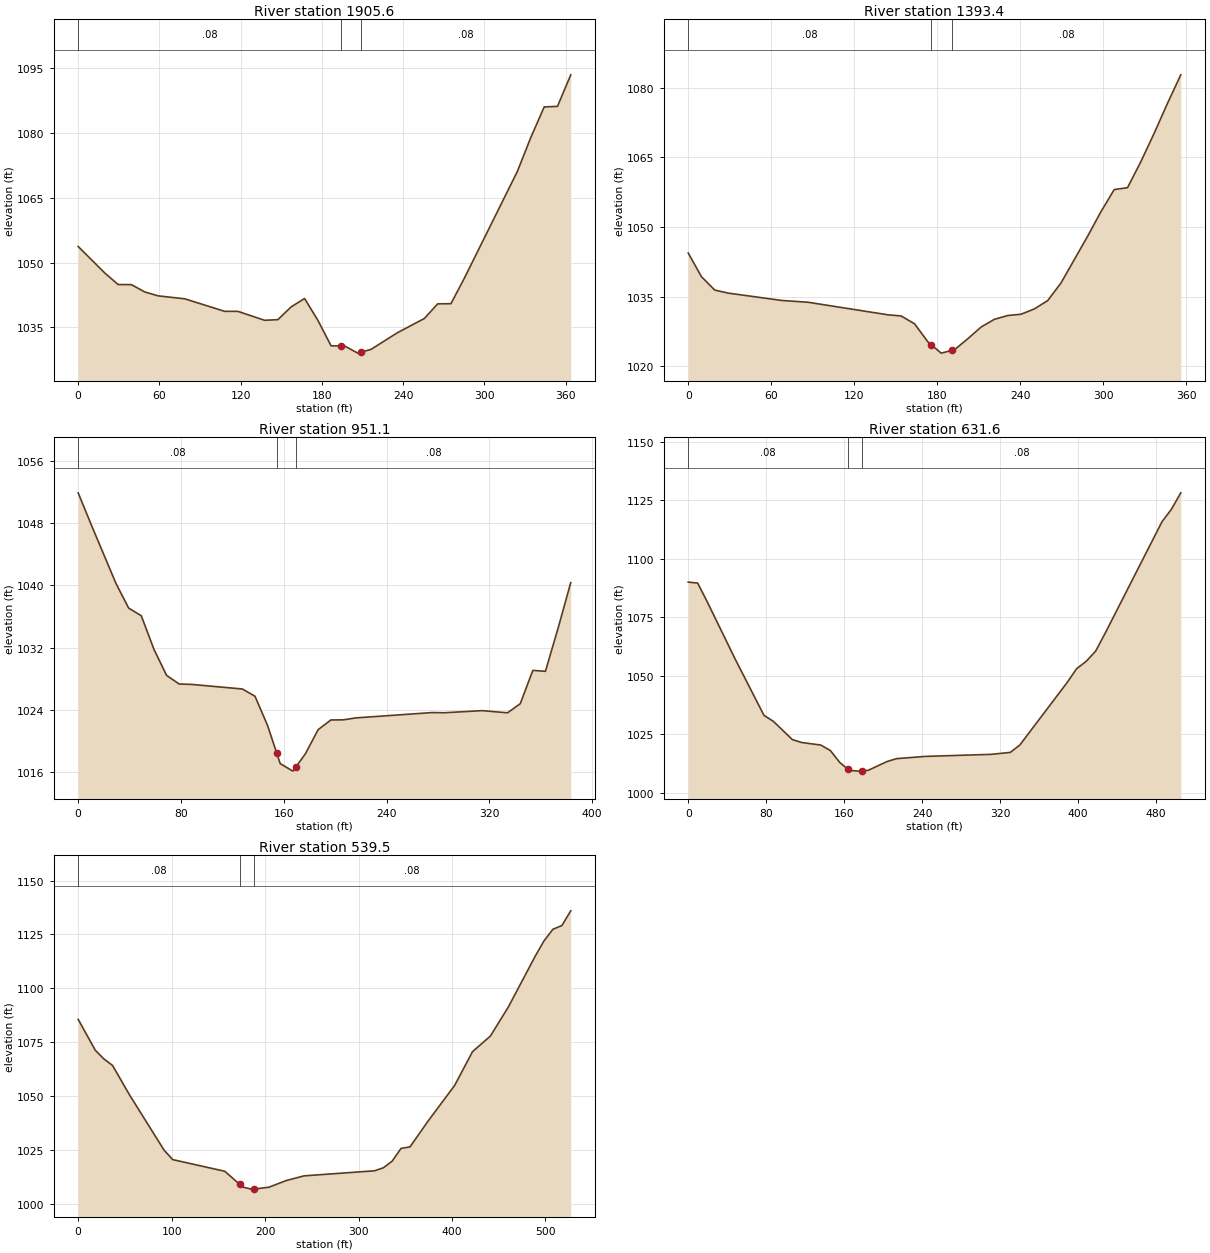
Type RM Length L Ch R = 1 ,1905.6  ,511.1,512,512.9
XS GIS Cut Line= 2
     1736780.973      274950.104      1736779.94      275313.935
#Sta/Elev= 30
       0 1053.72    19.7 1047.56    29.5  1044.9    39.3 1044.88    49.2 1043.18
      59 1042.28    78.7 1041.59   108.2 1038.69     118 1038.68   137.7 1036.61
   147.5 1036.76   157.3 1039.72   167.2 1041.66     177 1036.64   186.8 1030.69
   193.8 1030.68   196.7 1030.67   206.5    1029   208.8  1029.2   216.3 1029.87
     236 1033.77   255.7 1037.03   265.5 1040.42   275.3 1040.46   285.2 1046.35
   324.5  1071.2   334.3 1078.99   344.2 1086.07     354  1086.2   363.8 1093.51
#Mann= 3 , 0 , 0
       0     .08       0   193.8    .045       0   208.8     .08       0
#XS Ineff= 2 , 0
          167.24  1041.5
Permanent Ineff=
       F       F
Bank Sta=193.8,208.8
XS Rating Curve= 0 ,0
Exp/Cntr=0.3,0.1

Type RM Length L Ch R = 1 ,1393.4  ,440.9,442.3,443.8
XS GIS Cut Line= 2
     1736280.925      274958.334      1736264.76      275313.935
#Sta/Elev= 30
       0 1044.42     9.6  1039.3    19.2 1036.43    28.9 1035.78    67.4  1034.2
    86.6 1033.81   144.3 1031.11   153.9 1030.86   163.6 1029.17   173.2  1025.3
   175.8 1024.64   182.8 1022.86   190.8 1023.46   192.4 1023.58     202 1025.94
   211.7 1028.48   221.3 1030.14   230.9 1030.95   240.5 1031.23   250.1 1032.36
   259.8 1034.16   269.4 1037.95   288.6 1047.98   298.2 1053.25   307.9 1058.06
   317.5 1058.47   327.1 1064.04   336.7 1070.14   346.4 1076.63     356 1082.76
#Mann= 3 , 0 , 0
       0     .08       0   175.8    .045       0   190.8     .08       0
Bank Sta=175.8,190.8
XS Rating Curve= 0 ,0
Exp/Cntr=0.3,0.1

Type RM Length L Ch R = 1 ,951.1   ,317.3,319.5,321.6
XS GIS Cut Line= 2
     1735849.775      274962.334     1735807.794      275343.306
#Sta/Elev= 30
       0 1051.87     9.8 1047.92    29.5  1040.2    39.3 1037.06    49.1 1036.08
      59 1031.76    68.8 1028.42    78.6 1027.31    88.4 1027.26   127.8 1026.67
   137.6 1025.74   147.4 1021.98   154.6 1018.39   157.2 1017.09   167.1 1016.12
   169.6 1016.69   176.9 1018.37   186.7 1021.44   196.6 1022.69   206.4 1022.71
   216.2 1022.96   275.2 1023.64     285 1023.62   314.5 1023.89   334.1 1023.61
     344 1024.78   353.8 1029.06   363.6 1028.94   373.4 1034.46   383.3 1040.33
#Mann= 3 , 0 , 0
       0     .08       0   154.6    .045       0   169.6     .08       0
Bank Sta=154.6,169.6
XS Rating Curve= 0 ,0
Exp/Cntr=0.3,0.1

Type RM Length L Ch R = 1 ,631.6   ,101.8,92.1,82.2
XS GIS Cut Line= 2
     1735552.975      274900.365     1735449.911      275395.077
#Sta/Elev= 30
       0 1089.95     9.7 1089.54    19.4 1081.64    48.6  1056.7    77.7    1033
    87.5 1030.38   106.9  1022.6   116.6 1021.36     136 1020.29   145.8 1017.95
   155.5 1012.84   163.7    1010   165.2 1009.48   174.9 1009.14   178.7 1009.27
   184.6 1009.48   204.1 1013.26   213.8 1014.48     243 1015.43     311 1016.32
   330.4 1017.15   340.1 1020.26   388.7 1047.02   398.4  1052.9   408.2 1056.07
   417.9 1060.41   427.6 1067.99   485.9 1115.68   495.6 1121.06   505.3 1128.13
#Mann= 3 , 0 , 0
       0     .08       0   163.7    .045       0   178.7     .08       0
Bank Sta=163.7,178.7
XS Rating Curve= 0 ,0
Exp/Cntr=0.3,0.1

Type RM Length L Ch R = 1 ,539.5   ,548.5,539.3,530.4
XS GIS Cut Line= 4
     1735445.778      274877.983     1735417.754      275013.136
     1735461.773      275206.126      1735427.34      275394.136
#Sta/Elev= 30
       0 1085.58    18.4 1071.17    27.6 1067.15    36.8 1064.15    55.2 1050.29
      92 1024.76   101.2 1020.39   156.9 1014.98   172.9 1008.87   175.7 1007.69
   185.2 1006.68   187.9 1006.68     204 1007.55   222.9  1010.7   241.7 1012.84
   317.1  1015.2   326.6 1016.59     336 1019.68   345.5  1025.6   355.1 1026.32
   374.2 1038.15   402.9 1054.89     422 1070.57   441.1  1077.8   460.2 1091.21
   488.9 1114.77   498.4 1121.98     508 1127.42   517.6 1129.15   527.1    1136
#Mann= 3 , 0 , 0
       0     .08       0   172.9    .045       0   187.9     .08       0
Bank Sta=172.9,187.9
XS Rating Curve= 0 ,0
Exp/Cntr=0.3,0.1

Chan Stop Cuts=-1
Use User Specified Reach Order=0
Composite Channel Slope=5